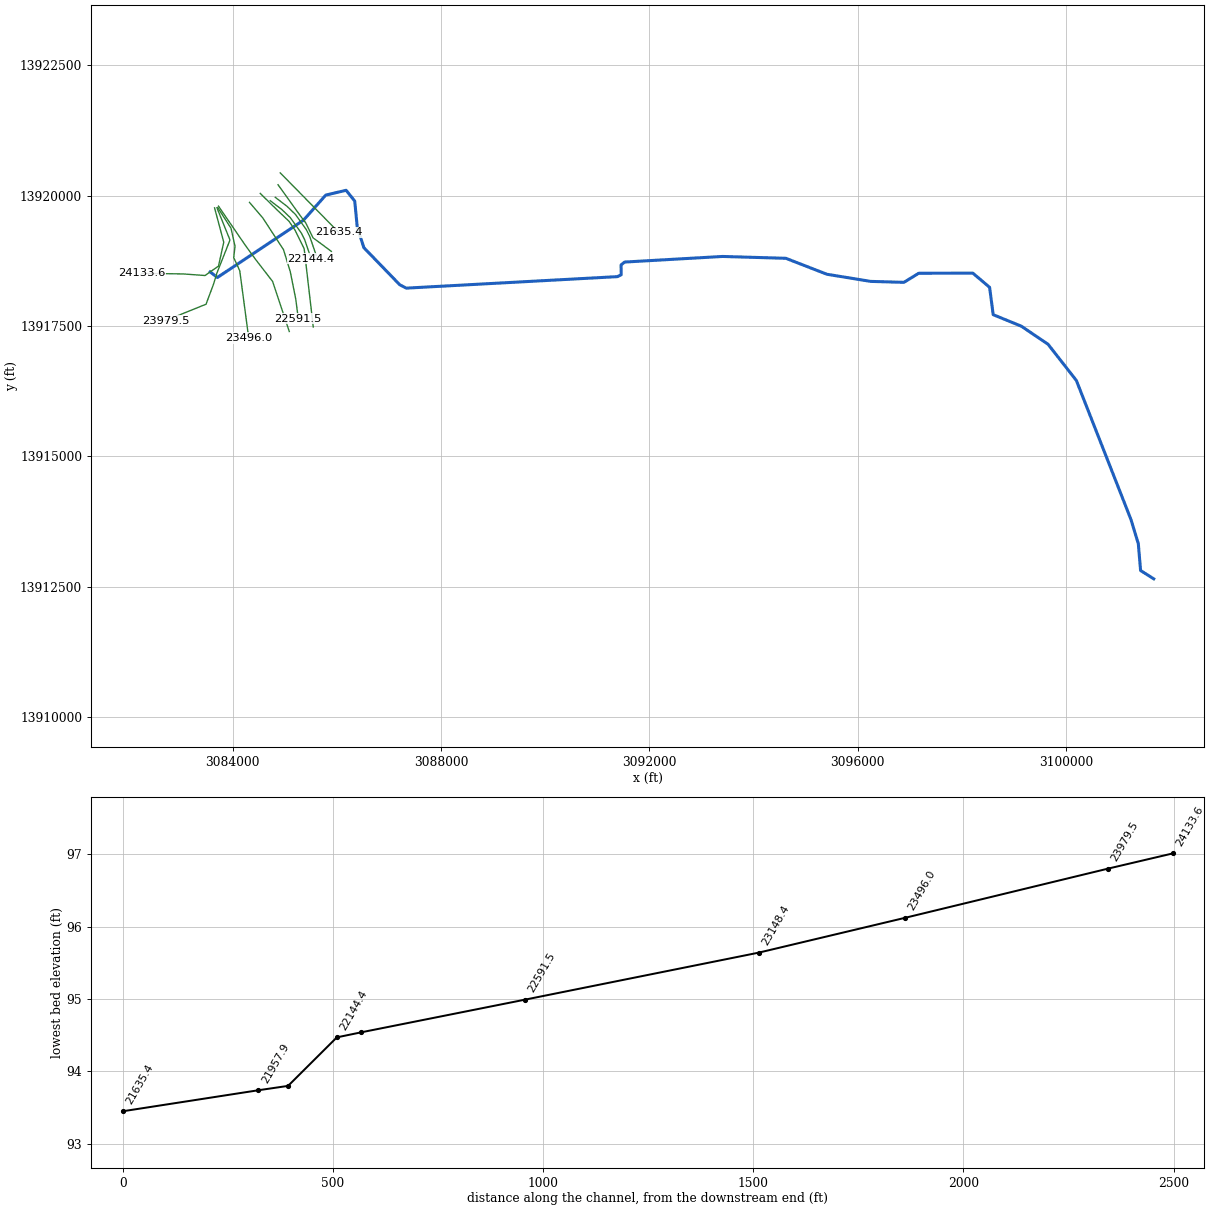
--- P145-00-00.PRJ (project) ---

Proj Title=P145-00-00
Current Plan=p02
Default Exp/Contr=.3,.1
English Units
Geom File=g01
Flow File=f01
Flow File=f02
Plan File=p01
Plan File=p02
Y Axis Title=Elevation
X Axis Title(PF)=Main Channel Distance
X Axis Title(XS)=Station
BEGIN DESCRIPTION:
Greens and Halls Bayou Watershed
North Fork Greens Bayou
HCFCD Unit P145-00-00
Flood Hazard Model
10, 2, 1, 0.2% Event
Filename P145-00-00.prj
Prepared by:  Watershed Concepts  Date:
Reviewed by:                      Date:
STATUS FINAL
END DESCRIPTION:
DSS Export Rating Curves= 0
DSS Export Rating Curve Sorted= 0
DSS Export Volume Flow Curves= 0
DXF OffsetX= 0
DXF OffsetY= 0
DXF ScaleX= 1
DXF ScaleY= 10

--- P145-00-00.p02 (plan) ---

Plan Title=Floodway
Version=Version 3.0.1  Mar 2001
Short Identifier=Floodway0607
Geom File=g01
Flow File=f02
Subcritical Flow
K Sum by GR= 0
Std Step Tol= 0.01
Critical Tol= 0.01
Num of Std Step Trials= 20
Max Error Tol= 0.3
Flow Tol Ratio= 0.001
Split Flow NTrial= 30
Split Flow Tol= 0.02
Split Flow Ratio= 0.02
Log Output Level= 0
Friction Slope Method= 1
Unsteady Friction Slope Method= 2
Parabolic Critical Depth
Global Vel Dist= 0 , 0 , 0
Global Log Level= 0
CheckData=True
Encroach Param=-1 ,0,0, 2
Encroach River=P145-00-00
Encroach Reach=Reach - 1
Encroach Node=24133.6
       1  4960.5  5035.1
Encroach Node=23979.5
       1  4955.5  5041.3
Encroach Node=23496.0
       1  4955.5    5054
Encroach Node=23148.4
       1  4955.5  5041.3
Encroach Node=22591.5
       1  4955.5  5041.3
Encroach Node=22202.7
       1  4954.6    5120
Encroach Node=22144.4
       1  4954.7    5120
Encroach Node=22086.4
       1  4954.7    5120
Encroach Node=22028.4
       1  4954.7    5120
Encroach Node=21957.9
       1 4954.01    5070
Encroach Node=21635.4
       1 4954.01 5039.81
Encroach Node=21624.9
       1 4954.01 5039.81
Encroach Node=21614.4
       1 4954.01 5039.81
Encroach Node=20931.8
       1  4974.9  5061.1
Encroach Node=20769.2
       1  4974.9  5061.1
Encroach Node=20743.7
       1  4974.9  5061.1
Encroach Node=20718.2
       1  4974.9  5061.1
Encroach Node=20419.2
       1 4953.94 5044.84
Encroach Node=19976.4
       1 4953.94 5044.84
Encroach Node=19964.9
       1 4953.94 5044.84
Encroach Node=19953.4
       1 4953.94 5044.84
Encroach Node=19627.6
       1  4958.2  5048.7
Encroach Node=18899.7
       1  4965.2  5051.8
Encroach Node=18779.9
       1  4965.2  5051.8
Encroach Node=18709.9
       1  4965.2  5051.8
Encroach Node=18639.9
       1  4965.2  5051.8
Encroach Node=18276.2
       1    4958  5049.7
Encroach Node=17985.1
       1    4958  5049.7
Encroach Node=17466.1
       1  4955.5  5047.2
Encroach Node=16892.5
       1  4955.5  5047.2
Encroach Node=15911.9
       1  4961.7  5046.4
Encroach Node=15413.4
       1  4960.8  5046.3
Encroach Node=14858.4
       1  4960.8  5046.3
Encroach Node=14460.0
       1  4964.2  5053.5
Encroach Node=14201.6
       1  4964.2  5053.5
Encroach Node=13898.8
       1  4964.2  5053.5
Encroach Node=13391.9
       1  4956.4  5040.6
Encroach Node=12779.7
       1  4956.4  5040.6
Encroach Node=11866.3
       1  4944.3  5049.6
Encroach Node=11144.9
       1  4945.8  5044.5
Encroach Node=10650.5
       1  4945.8  5044.5
Encroach Node=9612.9
       1  4943.5  5084.1
Encroach Node=8854.8
       1  4920.9  5067.7
Encroach Node=8621.3
       1  4920.9  5067.7
Encroach Node=8565.8
       1  4920.9  5067.7
Encroach Node=8510.3
       1  4920.9  5067.7
Encroach Node=7888.3
       1  4907.4  5060.5
Encroach Node=7351.8
       1  4947.5  5096.2
Encroach Node=6810.6
       1  4947.5  5096.2
Encroach Node=6390.1
       1  4934.3  5078.5
Encroach Node=5763.2
       1  4934.3  5078.5
Encroach Node=5243.0
       1  4925.1  5072.3
Encroach Node=4676.2
       1  4925.1  5072.3
Encroach Node=4240.2
       1  4929.4 5076.65
Encroach Node=3930.8
       1 4936.05 5076.65
Encroach Node=3779.1
       1 4936.05 5076.65
Encroach Node=3768.6
       1 4936.05 5076.65
Encroach Node=3767.9
       1    4936  5076.6
Encroach Node=3709.9
       1    4936  5076.6
Encroach Node=3651.9
       1    4936  5076.6
Encroach Node=3215.5
       1  4908.1  5067.6
Encroach Node=2475.6
       1  4918.3  5075.8
Encroach Node=2315.9
       1  4918.3  5075.8
Encroach Node=2279.6
       1  4918.3  5075.8
Encroach Node=2243.3
       1  4918.3  5075.8
Encroach Node=1761.3
       1  4928.8  5072.1
Encroach Node=973.3
       1  4928.8  5072.1
Encroach Node=204.0
       1 4911.94 5060.14
Encroach Node=193.5
       1 4911.94 5060.14
Encroach Node=183.0
       1 4911.94 5060.14
Encroach Node=98.6
       1 4911.94 5060.14
Encroach Reach=P145-00-00_0001
Encroach Node=24133.6
       1  4960.5  5035.1
Encroach Node=23979.5
       1  4955.5  5041.3
Encroach Node=23496.0
       1  4955.5    5054
Encroach Node=23148.4
       1  4955.5  5041.3
Encroach Node=22591.5
       1  4955.5  5041.3
Encroach Node=22202.7
       1  4954.6    5120
Encroach Node=22144.4
       1  4954.7    5120
Encroach Node=22086.4
       1  4954.7    5120
Encroach Node=22028.4
       1  4954.7    5120
Encroach Node=21957.9
       1 4954.01    5070
Encroach Node=21635.4
       1 4954.01 5039.81
Encroach Node=21624.9
       1 4954.01 5039.81
Encroach Node=21614.4
       1 4954.01 5039.81
Encroach Node=20931.8
       1  4974.9  5061.1
Encroach Node=20769.2
       1  4974.9  5061.1
Encroach Node=20743.7
       1  4974.9  5061.1
Encroach Node=20718.2
       1  4974.9  5061.1
Encroach Node=20419.2
       1 4953.94 5044.84
Encroach Node=19976.4
       1 4953.94 5044.84
Encroach Node=19964.9
       1 4953.94 5044.84
Encroach Node=19953.4
       1 4953.94 5044.84
Encroach Node=19627.6
       1  4958.2  5048.7
Encroach Node=18899.7
       1  4965.2  5051.8
Encroach Node=18779.9
       1  4965.2  5051.8
Encroach Node=18709.9
       1  4965.2  5051.8
Encroach Node=18639.9
       1  4965.2  5051.8
Encroach Node=18276.2
       1    4958  5049.7
Encroach Node=17985.1
       1    4958  5049.7
Encroach Node=17466.1
       1  4955.5  5047.2
Encroach Node=16892.5
       1  4955.5  5047.2
Encroach Node=15911.9
       1  4961.7  5046.4
Encroach Node=15413.4
       1  4960.8  5046.3
Encroach Node=14858.4
       1  4960.8  5046.3
Encroach Node=14460.0
       1  4964.2  5053.5
Encroach Node=14201.6
       1  4964.2  5053.5
Encroach Node=13898.8
       1  4964.2  5053.5
Encroach Node=13391.9
       1  4956.4  5040.6
Encroach Node=12779.7
       1  4956.4  5040.6
Encroach Node=11866.3
       1  4944.3  5049.6
Encroach Node=11144.9
       1  4945.8  5044.5
Encroach Node=10650.5
       1  4945.8  5044.5
Encroach Node=9612.9
       1  4943.5  5084.1
Encroach Node=8854.8
       1  4920.9  5067.7
Encroach Node=8621.3
       1  4920.9  5067.7
Encroach Node=8565.8
       1  4920.9  5067.7
Encroach Node=8510.3
       1  4920.9  5067.7
Encroach Node=7888.3
       1  4907.4  5060.5
Encroach Node=7351.8
       1  4947.5  5096.2
Encroach Node=6810.6
       1  4947.5  5096.2
Encroach Node=6390.1
       1  4934.3  5078.5
Encroach Node=5763.2
       1  4934.3  5078.5
Encroach Node=5243.0
       1  4925.1  5072.3
Encroach Node=4676.2
       1  4925.1  5072.3
Encroach Node=4240.2
       1  4929.4 5076.65
Encroach Node=3930.8
       1 4936.05 5076.65
Encroach Node=3779.1
       1 4936.05 5076.65
Encroach Node=3768.6
       1 4936.05 5076.65
Encroach Node=3767.9
       1    4936  5076.6
Encroach Node=3709.9
       1    4936  5076.6
Encroach Node=3651.9
       1    4936  5076.6
Encroach Node=3215.5
       1  4908.1  5067.6
Encroach Node=2475.6
       1  4918.3  5075.8
Encroach Node=2315.9
       1  4918.3  5075.8
Encroach Node=2279.6
       1  4918.3  5075.8
Encroach Node=2243.3
       1  4918.3  5075.8
Encroach Node=1761.3
       1  4928.8  5072.1
Encroach Node=973.3
       1  4928.8  5072.1
Encroach Node=204.0
       1 4911.94 5060.14
Encroach Node=193.5
       1 4911.94 5060.14
Encroach Node=183.0
       1 4911.94 5060.14
Encroach Node=98.6
       1 4911.94 5060.14
Computation Interval=1HOUR
Output Interval=1HOUR
Run HTab= 0
Run UNet= 0
Run PostProcess= 0
UNET Theta= 1
UNET ZTol= 0.02
UNET ZSATol= 0.1
UNET MxIter= 20
UNET MaxInSteps= 20
UNET DtIC= 0
UNET DtMin= 0
UNET MaxCRTS= 20
UNET WFStab= 2
UNET SFStab= 1
UNET WFX= 1
UNET SFX= 1
UNET Convert EG Bridges=-1
UNET Use Existing IB Tables=-1
Instantaneous Interval=1HOUR
Write IC File= 0
Write Velocity= 0
Write Detailed= 0

--- P145-00-00.p01 (plan) ---

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Plan Title=FEMA Effective June 2007
Short Identifier=FEMAeff0607
Geom File=g01
Flow File=f01
Encroach Param=-1 ,0,0, 0

--- P145-00-00.f02 (steady flow) ---

Flow Title= Floodway
Number of Profiles= 2
Profile Names=1PCT_100yr, 1PCTFloodway_100yrFW
River Rch & RM=P145-00-00,P145-00-00_0001,24133.6
     866     866
River Rch & RM=P145-00-00,P145-00-00_0001,23979.5
     942     942
River Rch & RM=P145-00-00,P145-00-00_0001,23148.4
    1036    1036
River Rch & RM=P145-00-00,P145-00-00_0001,22202.7
    1042    1042
River Rch & RM=P145-00-00,P145-00-00_0001,22144.4
    1089    1089
River Rch & RM=P145-00-00,P145-00-00_0001,21957.9
    1263    1263
River Rch & RM=P145-00-00,P145-00-00_0001,21635.4
    1273    1273
River Rch & RM=P145-00-00,P145-00-00_0001,20931.8
    1752    1752
River Rch & RM=P145-00-00,P145-00-00_0001,20769.2
    1812    1812
River Rch & RM=P145-00-00,P145-00-00_0001,20419.2
    1890    1890
River Rch & RM=P145-00-00,P145-00-00_0001,19976.4
    1954    1954
River Rch & RM=P145-00-00,P145-00-00_0001,19627.6
    2095    2095
River Rch & RM=P145-00-00,P145-00-00_0001,18899.7
    2119    2119
River Rch & RM=P145-00-00,P145-00-00_0001,18779.9
    2191    2191
River Rch & RM=P145-00-00,P145-00-00_0001,17985.1
    2239    2239
River Rch & RM=P145-00-00,P145-00-00_0001,17466.1
    2293    2293
River Rch & RM=P145-00-00,P145-00-00_0001,16892.5
    2389    2389
River Rch & RM=P145-00-00,P145-00-00_0001,15911.9
    2440    2440
River Rch & RM=P145-00-00,P145-00-00_0001,15413.4
    2497    2497
River Rch & RM=P145-00-00,P145-00-00_0001,14858.4
    2539    2539
River Rch & RM=P145-00-00,P145-00-00_0001,14460
    2600    2600
River Rch & RM=P145-00-00,P145-00-00_0001,13898.8
    2655    2655
River Rch & RM=P145-00-00,P145-00-00_0001,13391.9
    2724    2724
River Rch & RM=P145-00-00,P145-00-00_0001,12779.7
    2831    2831
River Rch & RM=P145-00-00,P145-00-00_0001,11866.3
    3739    3739
River Rch & RM=P145-00-00,P145-00-00_0001,9612.9
    7029    7029
River Rch & RM=P145-00-00,P145-00-00_0001,7351.8
    7324    7324
River Rch & RM=P145-00-00,P145-00-00_0001,5243
    7618    7618
River Rch & RM=P145-00-00,P145-00-00_0001,3215.5
    7957    7957
River Rch & RM=P145-00-00,P145-00-00_0001,973.3
    8094    8094
Boundary for River Rch & Prof#=P145-00-00,P145-00-00_0001, 1
Up Type= 0
Dn Type= 3
Dn Slope= 0.00195
Boundary for River Rch & Prof#=P145-00-00,P145-00-00_0001, 2
Up Type= 0
Dn Type= 1
Dn Known WS=87.27

--- P145-00-00.f01 (steady flow) ---

Flow Title= FEMA Effective June 2007
Number of Profiles= 4
Profile Names=10PCT_10yr, 2PCT_50yr, 1PCT_100yr, 0.2PCT_500yr
River Rch & RM=P145-00-00,P145-00-00_0001,24133.6
     523     750     866    1190
River Rch & RM=P145-00-00,P145-00-00_0001,23979.5
     569     815     942    1293
River Rch & RM=P145-00-00,P145-00-00_0001,23148.4
     626     897    1036    1422
River Rch & RM=P145-00-00,P145-00-00_0001,22202.7
     629     902    1042    1431
River Rch & RM=P145-00-00,P145-00-00_0001,22144.4
     657     942    1089    1495
River Rch & RM=P145-00-00,P145-00-00_0001,21957.9
     759    1092    1263    1736
River Rch & RM=P145-00-00,P145-00-00_0001,21635.4
     765    1101    1273    1749
River Rch & RM=P145-00-00,P145-00-00_0001,20931.8
    1043    1512    1752    2411
River Rch & RM=P145-00-00,P145-00-00_0001,20769.2
    1077    1564    1812    2495
River Rch & RM=P145-00-00,P145-00-00_0001,20419.2
    1122    1633    1890    2607
River Rch & RM=P145-00-00,P145-00-00_0001,19976.4
    1159    1689    1954    2698
River Rch & RM=P145-00-00,P145-00-00_0001,19627.6
    1240    1812    2095    2899
River Rch & RM=P145-00-00,P145-00-00_0001,18899.7
    1254    1833    2119    2933
River Rch & RM=P145-00-00,P145-00-00_0001,18779.9
    1295    1895    2191    3028
River Rch & RM=P145-00-00,P145-00-00_0001,17985.1
    1323    1936    2239    3092
River Rch & RM=P145-00-00,P145-00-00_0001,17466.1
    1354    1982    2293    3164
River Rch & RM=P145-00-00,P145-00-00_0001,16892.5
    1409    2065    2389    3291
River Rch & RM=P145-00-00,P145-00-00_0001,15911.9
    1438    2108    2440    3358
River Rch & RM=P145-00-00,P145-00-00_0001,15413.4
    1470    2157    2497    3434
River Rch & RM=P145-00-00,P145-00-00_0001,14858.4
    1494    2193    2539    3489
River Rch & RM=P145-00-00,P145-00-00_0001,14460
    1528    2245    2600    3569
River Rch & RM=P145-00-00,P145-00-00_0001,13898.8
    1560    2293    2655    3642
River Rch & RM=P145-00-00,P145-00-00_0001,13391.9
    1599    2352    2724    3733
River Rch & RM=P145-00-00,P145-00-00_0001,12779.7
    1660    2443    2831    3873
River Rch & RM=P145-00-00,P145-00-00_0001,11866.3
    2174    3218    3739    5152
River Rch & RM=P145-00-00,P145-00-00_0001,9612.9
    4135    6126    7029    9554
River Rch & RM=P145-00-00,P145-00-00_0001,7351.8
    4320    6392    7324    9834
River Rch & RM=P145-00-00,P145-00-00_0001,5243
    4507    6658    7618   10112
River Rch & RM=P145-00-00,P145-00-00_0001,3215.5
    4723    6966    7957   10428
River Rch & RM=P145-00-00,P145-00-00_0001,973.3
    4810    7090    8094   10554
Boundary for River Rch & Prof#=P145-00-00,P145-00-00_0001, 1
Up Type= 0
Dn Type= 3
Dn Slope= 0.00195
Boundary for River Rch & Prof#=P145-00-00,P145-00-00_0001, 2
Up Type= 0
Dn Type= 3
Dn Slope= 0.00195
Boundary for River Rch & Prof#=P145-00-00,P145-00-00_0001, 3
Up Type= 0
Dn Type= 3
Dn Slope= 0.00195
Boundary for River Rch & Prof#=P145-00-00,P145-00-00_0001, 4
Up Type= 0
Dn Type= 3
Dn Slope= 0.00195

--- P145-00-00.g01 (geometry) ---

Geom Title=P145-00-00 June 2007
Version=Version 3.0.1  Mar 2001

River Reach=P145-00-00      ,P145-00-00_0001
Reach XY= 30
      3083571.08     13918536.82       3083710.2     13918430.76
      3085363.75       13919530.      3085789.75       13920010.
       3086180.5       13920102.      3086346.25       13919895.
       3086394.5       13919394.        3086522.       13919001.
      3087210.25       13918291.      3087335.25       13918226.
      3091386.78     13918446.43      3091461.74      13918482.9
      3091457.69     13918669.29        3091526.       13918726.
      3093406.65     13918833.39       3094621.5       13918798.
       3095409.5       13918492.      3096249.05     13918355.27
        3096888.       13918337.      3097170.75       13918511.
       3098209.5       13918514.      3098532.29     13918241.81
      3098601.17     13917717.09        3099142.       13917496.
        3099654.       13917150.      3100197.75       13916455.
      3101245.03     13913790.81       3101386.8     13913325.84
      3101430.25       13912812.        3101683.       13912652.

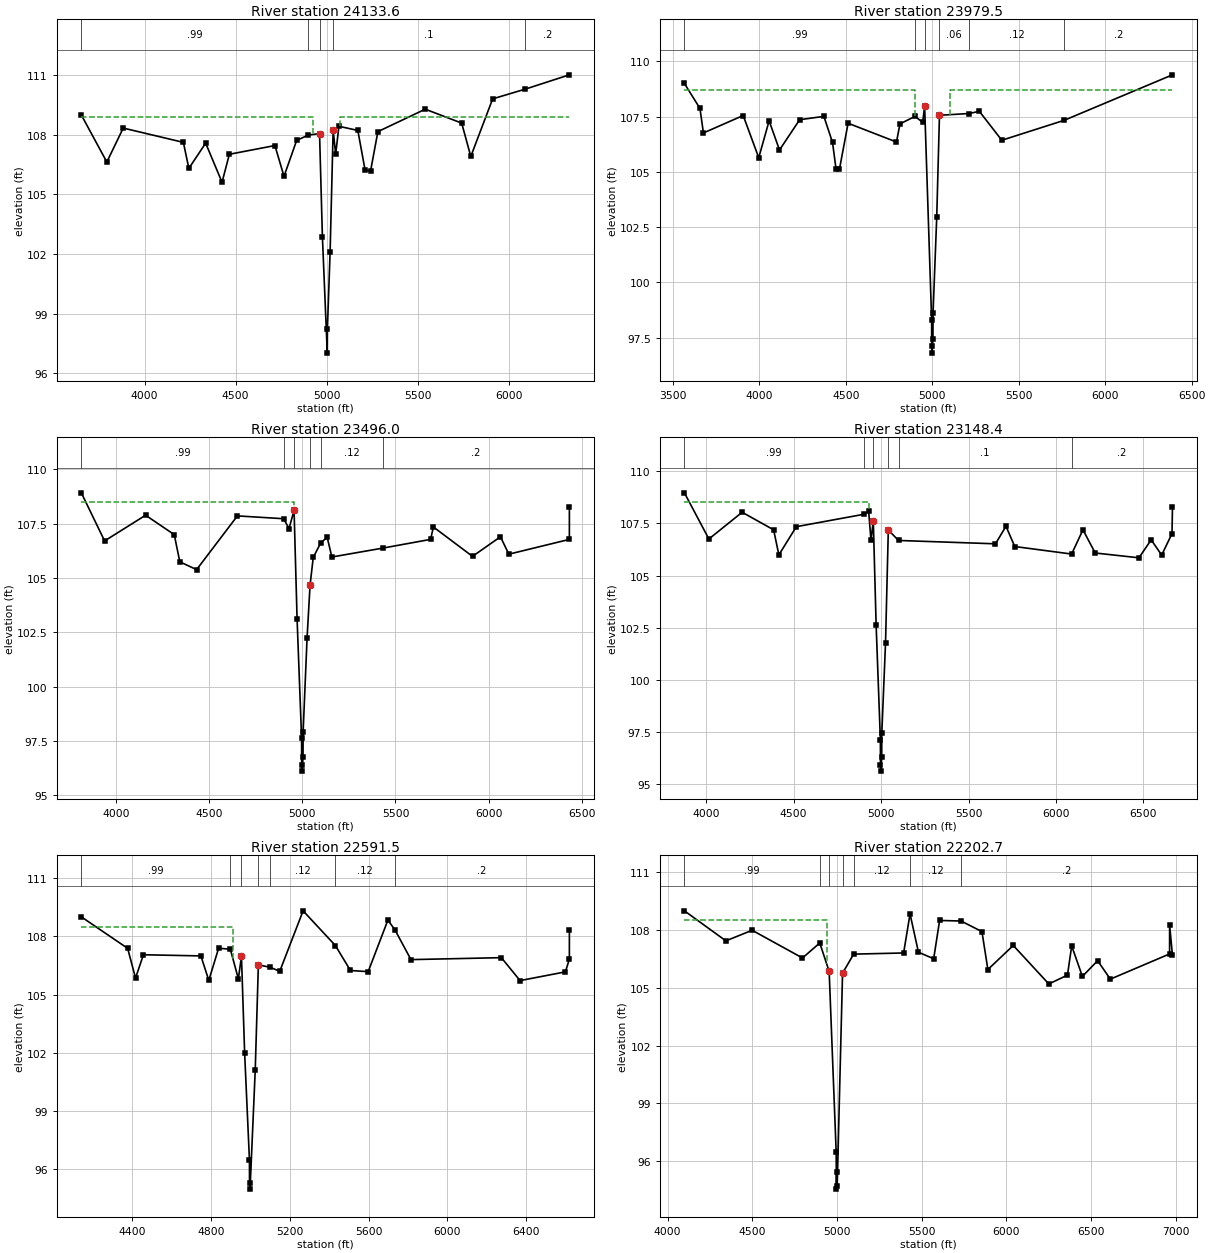
Type RM Length L Ch R = 1 ,24133.6 ,44.3,154.1,454.4
BEGIN DESCRIPTION:
Cross Section 24133.6
END DESCRIPTION:
XS GIS Cut Line= 6
      3083655.79     13919765.72      3083831.99     13919106.71
      3083731.23     13918648.25      3083472.19     13918467.95
       3083053.4     13918498.46      3082262.97     13918509.55
#Sta/Elev= 30
  3653.3     109  3793.3  106.63  3883.3  108.34  4213.3  107.62  4243.3  106.31
  4335.5  107.58  4425.5  105.61  4465.5  107.02  4715.5  107.46  4765.5  105.91
  4834.9  107.72  4899.7  107.99  4960.5  108.06  4976.1  102.88  5002.9   97.01
  5003.6   98.24  5018.5  102.12  5035.1  108.24  5048.9  107.02  5066.7  108.43
  5170.5  108.22  5210.5  106.22  5240.5  106.18  5280.5  108.16  5540.4  109.29
  5740.4  108.59  5790.4  106.91  5910.4  109.81  6089.1   110.3  6331.4  111.02
#Mann= 5 , 1 , 0
  3653.3     .99       0  4899.7      .1       0  4960.5     .04       0
  5035.1      .1       0  6089.1      .2       0
#XS Ineff= 2 , 0
       0    4927   108.9    5070       0   108.9
Permanent Ineff=
       F       F
Bank Sta=4960.5,5035.1
XS Rating Curve= 0
Exp/Cntr=.3,.1

Type RM Length L Ch R = 1 ,23979.5 ,384.7,483.5,746.8
BEGIN DESCRIPTION:
Cross Section 23979.5-Interpolated
END DESCRIPTION:
XS GIS Cut Line= 6
      3083700.99     13919766.88      3083951.68     13919149.03
      3083700.99     13918515.22      3083634.48     13918297.55
      3083492.03     13917917.68      3082711.73     13917602.43
#Sta/Elev= 30
  3565.9     109  3655.9  107.87  3675.9  106.76  3905.9  107.55  3995.9  105.64
  4055.9  107.31  4115.9  105.99  4232.7  107.36  4372.7  107.51  4422.7  106.33
  4442.7  105.15  4462.7  105.12  4512.7   107.2  4792.7  106.35  4812.7  107.17
  4899.9  107.51  4944.2  107.24  4955.5  107.96    4996    98.3  4996.4    97.1
  4999.1    96.8  5003.5   97.46  5004.1   98.61  5025.4  102.94  5041.3  107.56
  5212.8  107.64  5271.9  107.74  5401.9  106.43  5761.8  107.33  6389.1  109.39
#Mann= 6 , 1 , 0
  3565.9     .99       0  4899.9     .06       0  4955.5     .04       0
  5041.3     .06       0  5212.8     .12       0  5761.8      .2       0
#XS Ineff= 2 , 0
       0    4900   108.7    5100       0   108.7
Permanent Ineff=
       F       F
Bank Sta=4955.5,5041.3
XS Rating Curve= 0
Exp/Cntr=.3,.1

Type RM Length L Ch R = 1 ,23496.0 ,331.7,347.6,629.2
BEGIN DESCRIPTION:
Cross Section 23496.0 - Interpolated
END DESCRIPTION:
XS GIS Cut Line= 6
       3083716.8     13919769.34      3083971.26     13919375.65
      3084048.08     13919029.96      3084024.08      13918809.1
       3084139.3     13918559.44      3084311.13     13917270.77
#Sta/Elev= 30
  3813.4  108.91  3938.4   106.7  4158.4  107.88  4312.2  106.99  4342.2  105.74
  4432.2  105.38  4651.3  107.85  4899.2  107.72  4928.4  107.27  4955.5   108.1
  4971.7   103.1    4996   97.62  4996.4   96.42  4999.1   96.12  5003.5   96.78
  5004.1   97.93  5025.4  102.26  5041.3  104.66  5058.4  105.94  5099.2  106.62
  5133.4  106.86  5158.4  105.96  5432.2  106.37  5688.4  106.77  5703.4  107.34
  5913.4  105.99  6063.4  106.89  6108.4  106.09  6433.4  106.77  6433.5  108.27
#Mann= 6 , 1 , 0
  3813.4     .99       0  4899.2     .06       0  4955.5    .035       0
  5041.3     .06       0  5099.2     .12       0  5432.2      .2       0
#XS Ineff= 2 , 0
       0    4955   108.5               0
Permanent Ineff=
       F       F
Bank Sta=4955.5,5041.3
XS Rating Curve= 0
Exp/Cntr=.3,.1

Type RM Length L Ch R = 1 ,23148.4 ,558.5,556.9,382.8
BEGIN DESCRIPTION:
Cross Section 23148.4
END DESCRIPTION:
XS GIS Cut Line= 5
      3083731.23     13919797.11      3084245.98      13919047.6
      3084445.67     13918773.03      3084769.81     13918354.27
      3085089.72     13917394.52
#Sta/Elev= 30
  3875.7  108.96  4015.7  106.75  4205.7  108.03  4385.7  107.19  4415.7  105.99
  4515.7  107.34  4899.7  107.93  4929.1  108.07  4942.2  106.69  4955.5  107.62
  4971.7  102.62    4996   97.14  4996.4   95.94  4999.1   95.64  5003.5    96.3
  5004.1   97.45  5025.4  101.78  5041.3  107.18  5099.7  106.68    5654  106.52
    5714  107.36    5764  106.39  6089.1  106.03    6154  107.19    6224  106.08
    6474  105.85    6544  106.71    6604  105.98    6663  107.01  6665.7   108.3
#Mann= 6 , 1 , 0
  3875.7     .99       0  4899.7     .06       0  4955.5    .035       0
  5041.3     .06       0  5099.7      .1       0  6089.1      .2       0
#XS Ineff= 2 , 0
       0    4929   108.5               0
Permanent Ineff=
       F       F
Bank Sta=4955.5,5041.3
XS Rating Curve= 0
Exp/Cntr=.3,.1

Type RM Length L Ch R = 1 ,22591.5 ,391.7,388.8,357.5
BEGIN DESCRIPTION:
Cross Section 22591.5 - Interpolated
END DESCRIPTION:
XS GIS Cut Line= 6
      3084326.55     13919870.17      3084581.01     13919572.49
      3084979.51     13918962.74      3085109.15     13918540.24
      3085214.77     13918012.11      3085262.78     13917640.04
#Sta/Elev= 30
  4143.2     109  4378.2  107.38  4418.2  105.85  4458.2  107.05  4749.8  106.99
  4789.8  105.73  4839.8  107.39  4899.2  107.33  4939.8  105.81  4955.5  106.97
  4971.7  101.97    4996   96.49  4996.4   95.29  4999.1   94.99  5025.4  101.13
  5041.3  106.53  5099.2  106.41  5149.8   106.2  5268.2  109.31  5432.2  107.52
  5508.2  106.24  5598.2  106.18  5698.2  108.83  5733.6  108.34  5815.2   106.8
  6273.8   106.9  6368.8  105.72  6598.8  106.17  6618.8  106.83  6618.9  108.33
#Mann= 7 , 1 , 0
  4143.2     .99       0  4899.2     .06       0  4955.5    .035       0
  5041.3     .06       0  5099.2     .12       0  5432.2     .12       0
  5733.6      .2       0
#XS Ineff= 2 , 0
       0  4912.7   108.5               0
Permanent Ineff=
       F       F
Bank Sta=4955.5,5041.3
XS Rating Curve= 0
Exp/Cntr=.3,.1

Type RM Length L Ch R = 1 ,22202.7 ,54.3,58.3,95.8
BEGIN DESCRIPTION:
Cross Section 22202.7-Interpolated
END DESCRIPTION:
XS GIS Cut Line= 6
      3084532.52     13920042.37      3084830.13     13919750.06
      3085085.68     13919506.87      3085200.56     13919337.57
      3085375.91     13918980.82      3085550.36     13917480.87
#Sta/Elev= 30
  4099.8     109  4344.8  107.44  4499.8  107.99    4797  106.55  4899.2  107.33
  4954.6  105.85    4996   96.47  4997.5   94.54    4999   95.44    5002   94.69
  5033.7  105.76  5099.2  106.75  5394.3  106.81  5432.2  108.84  5481.8  106.85
  5571.8  106.51  5606.8   108.5  5733.6  108.47  5856.8  107.92  5891.8  105.95
  6041.8   107.2  6251.8   105.2  6361.8  105.66  6386.8  107.18  6449.9  105.59
  6539.9  106.41  6614.9  105.45  6964.9  106.76    6965  108.26  6981.9  106.68
#Mann= 7 , 1 , 0
  4099.8     .99       0  4899.2     .06       0  4954.6    .035       0
  5033.7     .06       0  5099.2     .12       0  5432.2     .12       0
  5733.6      .2       0
#XS Ineff= 2 , 0
       0    4940   108.5               0
Permanent Ineff=
       F       F
Bank Sta=4954.6,5033.7
XS Rating Curve= 0
Exp/Cntr=.5,.3

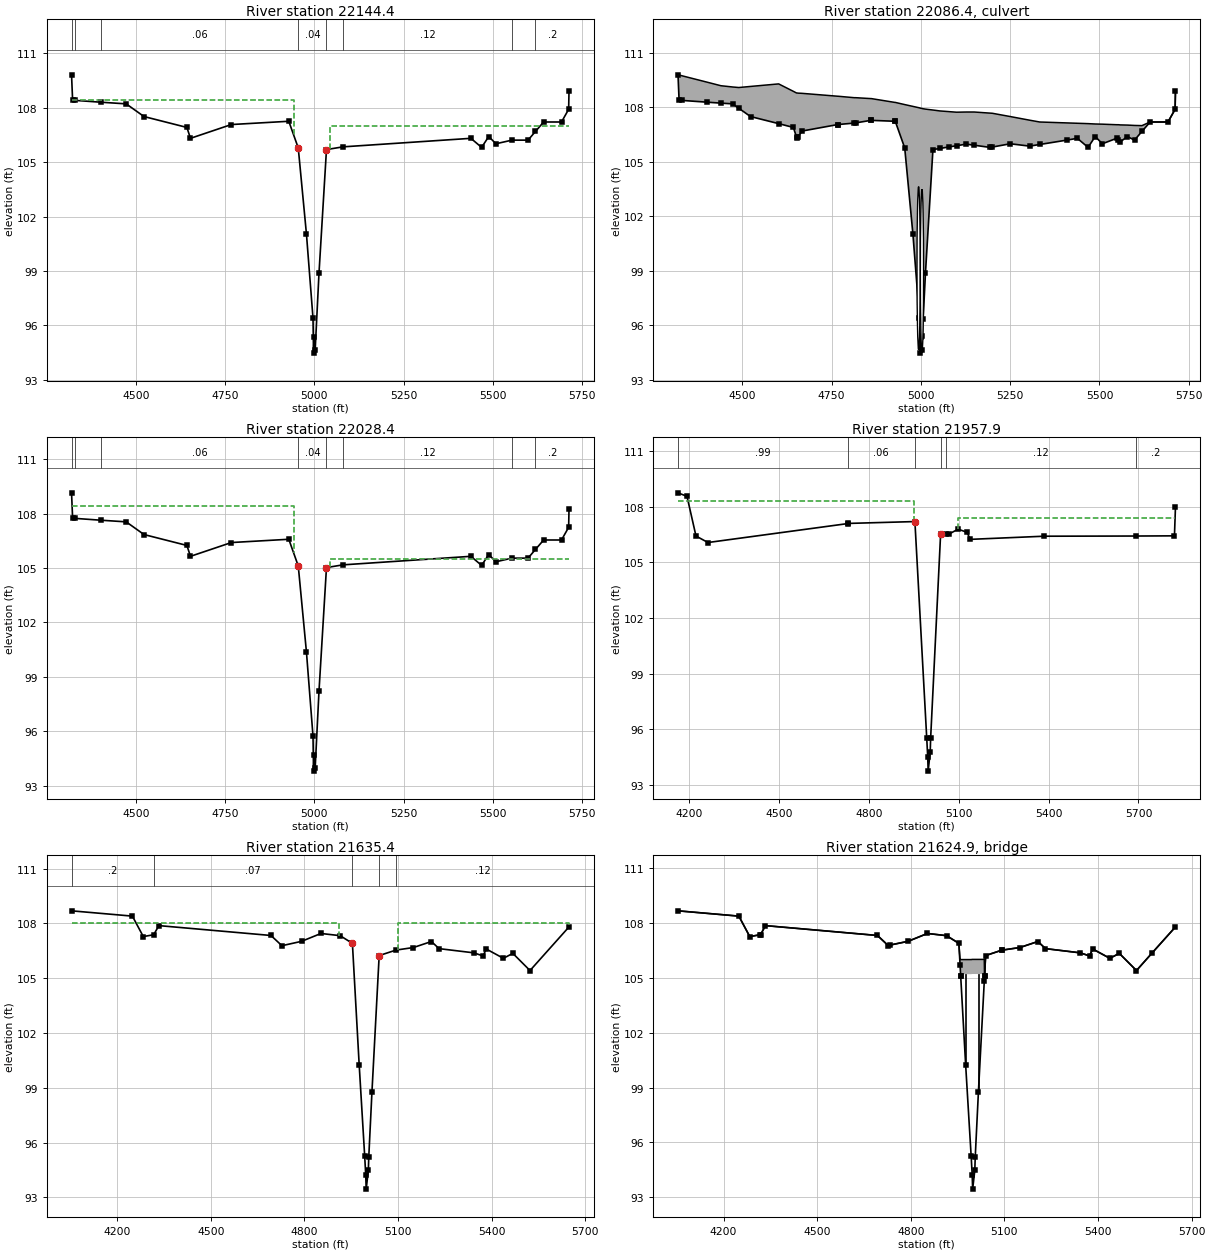
Type RM Length L Ch R = 1 ,22144.4 ,116,116,116
BEGIN DESCRIPTION:
Upstream Section of Bridge/Culvert/Weir
END DESCRIPTION:
XS GIS Cut Line= 6
       3084724.7     13919902.32       3084948.8     13919731.48
      3085108.54     13919578.38      3085319.33     13919285.51
      3085385.89     13919152.38      3085509.65     13918792.92
#Sta/Elev= 30
  4319.9  109.81  4322.9  108.41  4330.7   108.4  4402.4   108.3  4472.9  108.21
  4522.9  107.51  4642.9  106.91  4652.9  106.31  4767.4  107.07  4928.2  107.25
  4954.7  105.78  4977.7  101.02    4996    96.4  4997.5   94.47    4999   95.37
    5002   94.62  5012.8   98.89  5033.7  105.69    5080  105.84  5438.1  106.31
  5468.1  105.81  5488.1  106.41  5508.1  106.01  5553.1  106.21  5598.1  106.21
  5618.9  106.69  5641.8  107.21  5691.8  107.21  5711.8  107.91  5712.8  108.91
#Mann= 8 , 1 , 0
  4319.9      .2       0  4330.7      .1       0  4402.4     .06       0
  4954.7     .04       0  5033.7     .06       0    5080     .12       0
  5553.1      .1       0  5618.9      .2       0
#XS Ineff= 2 , 0
       0    4942   108.4    5043       0     107
Permanent Ineff=
       F       F
Bank Sta=4954.7,5033.7
XS Rating Curve= 0
Exp/Cntr=.5,.3

Type RM Length L Ch R = 2 ,22086.4 ,,,
BEGIN DESCRIPTION:
WALTERS ROAD
Structure ID: P45-10
END DESCRIPTION:
Bridge Culvert--1,0,-1,-1, 0
Deck Dist Width WeirC Skew NumUp NumDn MinLoCord MaxHiCord MaxSubmerge Is_Ogee
10,96,3,0, 57, 57, , , .95, 0, 1,1,,
  4319.9  4322.9  4330.7  4402.4  4439.9  4472.9  4489.9  4522.9  4601.7  4642.9
  4651.7  4652.9    4657    4667  4767.4    4768  4813.3  4817.3  4859.9  4861.3
  4927.1  4928.2  4954.7  4977.7    4996  4997.5    4999    5002  5003.9  5006.3
  5012.8  5033.7  5053.1    5080  5099.8  5126.8  5149.2  5193.3  5200.3  5250.3
  5304.4  5332.7  5408.1  5438.1  5468.1  5488.1  5508.1  5548.1  5553.1  5558.1
  5578.1  5598.1  5618.9  5641.8  5691.8  5711.8  5712.8
   109.8  109.79  109.75  109.39   109.2  109.13   109.1  109.16   109.3  108.89
   108.8   108.8  108.79  108.78  108.62  108.62  108.54  108.54  108.49  108.49
  108.28  108.28  108.16  108.06  107.98  107.97  107.96  107.95  107.94  107.93
  107.91  107.86  107.81  107.77  107.74  107.75  107.75  107.69  107.68   107.5
   107.3   107.2  107.15  107.13  107.11  107.09  107.08  107.05  107.05  107.04
  107.03  107.01     107   107.2   107.2   107.9   108.9
   109.8   108.4  108.39  108.29  108.24   108.2  107.96   107.5  107.11   106.9
  106.37   106.3   106.4   106.7  107.06  107.06  107.14  107.15  107.29  107.29
  107.24  107.24  105.77  101.01   96.39   94.46   95.36   94.61   95.41   96.35
   98.88  105.68  105.74  105.83  105.89  105.98  105.92   105.8  105.82     106
  105.87  105.96   106.2   106.3   105.8   106.4     106   106.3   106.2   106.1
   106.4   106.2  106.68   107.2   107.2   107.9   108.9
  4319.9  4322.9  4330.7  4402.4  4439.9  4472.9  4489.9  4522.9  4601.7  4642.9
  4651.7  4652.9    4657    4667  4767.4    4768  4813.3  4817.3  4859.9  4861.3
  4927.1  4928.2  4954.7  4977.7    4996  4997.5    4999    5002  5003.9  5006.3
  5012.8  5033.7  5053.1    5080  5099.8  5126.8  5149.2  5193.3  5200.3  5250.3
  5304.4  5332.7  5408.1  5438.1  5468.1  5488.1  5508.1  5548.1  5553.1  5558.1
  5578.1  5598.1  5618.9  5641.8  5691.8  5711.8  5712.8
   109.8  109.79  109.75  109.39   109.2  109.13   109.1  109.16   109.3  108.89
   108.8   108.8  108.79  108.78  108.62  108.62  108.54  108.54  108.49  108.49
  108.28  108.28  108.16  108.06  107.98  107.97  107.96  107.95  107.94  107.93
  107.91  107.86  107.81  107.77  107.74  107.75  107.75  107.69  107.68   107.5
   107.3   107.2  107.15  107.13  107.11  107.09  107.08  107.05  107.05  107.04
  107.03  107.01     107   107.2   107.2   107.9   108.9
  109.15  107.75  107.74  107.64  107.59  107.55  107.31  106.85  106.46  106.25
  105.72  105.65  105.75  106.05  106.41  106.41  106.49   106.5  106.64  106.64
  106.59  106.59  105.12  100.36   95.74   93.81   94.71   93.96   94.76    95.7
   98.23  105.03  105.09  105.18  105.24  105.33  105.27  105.15  105.17  105.35
  105.22  105.31  105.55  105.65  105.15  105.75  105.35  105.65  105.55  105.45
  105.75  105.55  106.03  106.55  106.55  107.25  108.25
BR Coef= 1 , 0 , 0 ,1.25, 0 ,,,.8,-1,2,0,
WSPro=,,,, 1 ,,,, 0 ,,,, 0 ,,,,-1 ,-1 ,-1 , 0 , 0 , 0 , 0 , 0
Culvert=1,9,,96,.025,.9,1,1,3,94.64,4993.6,94.36,4993.6,Culvert #1  , 0 ,10
Culvert Bottom n=.025
Culvert=1,9,,96,.025,.9,1,1,3,94.49,5003,94.51,5003,Culvert #2  , 0 ,10
Culvert Bottom n=.025
BR U #Sta/Elev= 57
  4319.9   109.8  4322.9   108.4  4330.7  108.39  4402.4  108.29  4439.9  108.24
  4472.9   108.2  4489.9  107.96  4522.9   107.5  4601.7  107.11  4642.9   106.9
  4651.7  106.37  4652.9   106.3    4657   106.4    4667   106.7  4767.4  107.06
    4768  107.06  4813.3  107.14  4817.3  107.15  4859.9  107.29  4861.3  107.29
  4927.1  107.24  4928.2  107.24  4954.7  105.77  4977.7  101.01    4996   96.39
  4997.5   94.46    4999   95.36    5002   94.61  5003.9   95.41  5006.3   96.35
  5012.8   98.88  5033.7  105.68  5053.1  105.74    5080  105.83  5099.8  105.89
  5126.8  105.98  5149.2  105.92  5193.3   105.8  5200.3  105.82  5250.3     106
  5304.4  105.87  5332.7  105.96  5408.1   106.2  5438.1   106.3  5468.1   105.8
  5488.1   106.4  5508.1     106  5548.1   106.3  5553.1   106.2  5558.1   106.1
  5578.1   106.4  5598.1   106.2  5618.9  106.68  5641.8   107.2  5691.8   107.2
  5711.8   107.9  5712.8   108.9
BR U #Mann= 8
  4319.9      .2  4330.7      .1  4402.4     .06  4954.7     .04  5033.7     .06
    5080     .12  5553.1      .1  5618.9      .2
BR U Banks=4954.7,5033.7
BR D #Sta/Elev= 57
  4319.9  109.15  4322.9  107.75  4330.7  107.74  4402.4  107.64  4439.9  107.59
  4472.9  107.55  4489.9  107.31  4522.9  106.85  4601.7  106.46  4642.9  106.25
  4651.7  105.72  4652.9  105.65    4657  105.75    4667  106.05  4767.4  106.41
    4768  106.41  4813.3  106.49  4817.3   106.5  4859.9  106.64  4861.3  106.64
  4927.1  106.59  4928.2  106.59  4954.7  105.12  4977.7  100.36    4996   95.74
  4997.5   93.81    4999   94.71    5002   93.96  5003.9   94.76  5006.3    95.7
  5012.8   98.23  5033.7  105.03  5053.1  105.09    5080  105.18  5099.8  105.24
  5126.8  105.33  5149.2  105.27  5193.3  105.15  5200.3  105.17  5250.3  105.35
  5304.4  105.22  5332.7  105.31  5408.1  105.55  5438.1  105.65  5468.1  105.15
  5488.1  105.75  5508.1  105.35  5548.1  105.65  5553.1  105.55  5558.1  105.45
  5578.1  105.75  5598.1  105.55  5618.9  106.03  5641.8  106.55  5691.8  106.55
  5711.8  107.25  5712.8  108.25
BR D #Mann= 8
  4319.9      .2  4330.7      .1  4402.4     .06  4954.7     .04  5033.7     .06
    5080     .12  5553.1      .1  5618.9      .2
BR D Banks=4954.7,5033.7
BC Design=,, 0 ,, 0 ,,,,,,

Type RM Length L Ch R = 1 ,22028.4 ,70.5,70.5,70.5
BEGIN DESCRIPTION:
Downstream Section of Bridge/Culvert/Weir
END DESCRIPTION:
XS GIS Cut Line= 6
      3084821.16     13919966.76      3085045.26     13919795.92
        3085205.     13919642.82      3085415.79     13919349.95
      3085482.35     13919216.82       3085606.1     13918857.36
#Sta/Elev= 30
  4319.9  109.14  4322.9  107.74  4330.7  107.73  4402.4  107.63  4472.9  107.54
  4522.9  106.84  4642.9  106.24  4652.9  105.64  4767.4   106.4  4928.2  106.58
  4954.7  105.11  4977.7  100.35    4996   95.73  4997.5    93.8    4999    94.7
    5002   93.95  5012.8   98.22  5033.7  105.02    5080  105.17  5438.1  105.64
  5468.1  105.14  5488.1  105.74  5508.1  105.34  5553.1  105.54  5598.1  105.54
  5618.9  106.02  5641.8  106.54  5691.8  106.54  5711.8  107.24  5712.8  108.24
#Mann= 8 , 1 , 0
  4319.9      .2       0  4330.7      .1       0  4402.4     .06       0
  4954.7     .04       0  5033.7     .06       0    5080     .12       0
  5553.1      .1       0  5618.9      .2       0
#XS Ineff= 2 , 0
       0    4942   108.4    5043       0   105.5
Permanent Ineff=
       F       F
Bank Sta=4954.7,5033.7
XS Rating Curve= 0
Exp/Cntr=.5,.3

Type RM Length L Ch R = 1 ,21957.9 ,335.6,322.5,320.1
BEGIN DESCRIPTION:
Cross Section 21957.9-Interpolated
END DESCRIPTION:
XS GIS Cut Line= 5
      3084874.04     13920208.29       3085309.4     13919603.62
      3085406.15     13919476.64      3085544.87       13919192.
      3085897.34     13918930.91
#Sta/Elev= 22
  4163.5  108.75  4193.5  108.56  4223.5  106.42  4263.5  106.07  4729.5  107.09
 4731.91   107.1 4954.01   107.2 4993.41   95.54 4996.71   94.52 4998.21   93.74
 5005.11   94.78 5006.51   95.51 5039.81  106.53  5059.1  106.53  5068.2  106.53
  5098.2  106.79  5128.2  106.62  5138.2  106.24  5384.9  106.41  5691.5  106.42
  5820.1  106.43  5823.5     108
#Mann= 6 , 1 , 0
  4163.5     .99       0  4729.5     .06       0 4954.01     .04       0
 5039.81     .06       0  5059.1     .12       0  5691.5      .2       0
#XS Ineff= 2 , 0
       0    4950   108.3  5098.2       0   107.4
Permanent Ineff=
       F       F
Bank Sta=4954.01,5039.81
XS Rating Curve= 0
Exp/Cntr=.5,.3

Type RM Length L Ch R = 1 ,21635.4 ,21,21,21
BEGIN DESCRIPTION:
Upstream Section of Bridge/Culvert/Weir
END DESCRIPTION:
XS GIS Cut Line= 2
      3084916.71     13920436.23      3086034.55     13919299.47
#Sta/Elev= 30
  4053.9  108.69  4248.9   108.4  4283.9  107.28  4317.1  107.38  4333.9  107.88
  4693.1  107.34  4728.1  106.78 4791.21  107.02 4853.31  107.45 4914.61  107.33
 4954.01  106.91 4975.71  100.27 4993.41   95.25 4996.71   94.23 4998.21   93.45
 5005.11   94.49 5006.51   95.22 5016.61   98.75 5039.81  106.24  5093.6  106.54
 5149.51  106.68 5207.31  107.01 5231.61  106.62  5342.9  106.39  5372.9  106.22
  5382.9   106.6  5437.9  106.09  5468.2  106.36  5523.2  105.42  5648.2  107.81
#Mann= 5 , 1 , 0
  4053.9      .2       0  4317.1     .07       0 4954.01     .04       0
 5039.81     .07       0  5093.6     .12       0
#XS Ineff= 2 , 0
       0    4911     108    5100       0     108
Permanent Ineff=
       F       F
Bank Sta=4954.01,5039.81
XS Rating Curve= 0
Exp/Cntr=.5,.3

Type RM Length L Ch R = 3 ,21624.9 ,,,
BEGIN DESCRIPTION:
9" PIPELINE
END DESCRIPTION:
Bridge Culvert--1,0,-1,-1, 0
Deck Dist Width WeirC Skew NumUp NumDn MinLoCord MaxHiCord MaxSubmerge Is_Ogee
10,1,2.6,0, 40, 40, , , .95, 0, 1,1,,
  4053.9  4248.9  4283.9  4317.1  4318.9  4333.9  4693.1  4728.1 4731.91 4791.21
 4853.31 4914.61 4954.01 4957.81 4959.82 4959.91 4975.71 4993.41 4996.71 4998.21
 5005.11 5006.51 5016.61 5035.41  5036.3 5036.41 5039.81 5092.41  5093.6 5149.51
 5207.31 5231.61  5342.9  5372.9  5382.9  5437.9  5468.2  5523.2  5573.2  5648.2
  108.68  108.39  107.27  107.37  107.38  107.87  107.33  106.77   106.8  107.01
  107.44  107.32   106.9  106.01  106.01  106.01  106.01  106.01  106.02  106.02
  106.02  106.02  106.02  106.02   105.1  105.13  106.23  106.53  106.53  106.67
     107  106.61  106.38  106.21  106.59  106.08  106.35  105.41  106.37   107.8
  108.68  108.39  107.27  107.37  107.38  107.87  107.33  106.77   106.8  107.01
  107.44  107.32   106.9  105.74  105.12  105.21  105.21  105.21  105.22  105.22
  105.22  105.22  105.22  105.22   105.1  105.13  106.23  106.53  106.53  106.67
     107  106.61  106.38  106.21  106.59  106.08  106.35  105.41  106.37   107.8
  4053.9  4248.9  4283.9  4317.1  4318.9  4333.9  4693.1  4728.1 4731.91 4791.21
 4853.31 4914.61 4954.01 4957.81 4959.82 4959.91 4975.71 4993.41 4996.71 4998.21
 5005.11 5006.51 5016.61 5035.41  5036.3 5036.41 5039.81 5092.41  5093.6 5149.51
 5207.31 5231.61  5342.9  5372.9  5382.9  5437.9  5468.2  5523.2  5573.2  5648.2
  108.68  108.39  107.27  107.37  107.38  107.87  107.33  106.77   106.8  107.01
  107.44  107.32   106.9  106.01  106.01  106.01  106.01  106.01  106.02  106.02
  106.02  106.02  106.02  106.02   105.1  105.13  106.23  106.53  106.53  106.67
     107  106.61  106.38  106.21  106.59  106.08  106.35  105.41  106.37   107.8
  108.68  108.39  107.27  107.37  107.38  107.87  107.33  106.77   106.8  107.01
  107.44  107.32   106.9  105.74  105.12  105.21  105.21  105.21  105.22  105.22
  105.22  105.22  105.22  105.22   105.1  105.13  106.23  106.53  106.53  106.67
     107  106.61  106.38  106.21  106.59  106.08  106.35  105.41  106.37   107.8
Pier Skew, UpSta & Num, DnSta & Num=  ,4975.7, 2 ,4975.7, 2 , 0 , 0 , 0 ,,
       1       1
   99.12  106.21
       1       1
   99.12  106.21
Pier Skew, UpSta & Num, DnSta & Num=  ,5016.6, 2 ,5016.6, 2 , 0 , 0 , 0 ,,
       1       1
   97.57  106.22
       1       1
   97.57  106.22
BR Coef= 1 , 1 , 0 ,1.25, 0 ,,,.8,0,2,0,
WSPro=,,,, 1 ,,,, 0 ,,,, 0 ,,,,-1 ,-1 ,-1 , 0 , 0 , 0 , 0 , 0
BR U #Sta/Elev= 40
  4053.9  108.68  4248.9  108.39  4283.9  107.27  4317.1  107.37  4318.9  107.38
  4333.9  107.87  4693.1  107.33  4728.1  106.77 4731.91   106.8 4791.21  107.01
 4853.31  107.44 4914.61  107.32 4954.01   106.9 4957.81  105.74 4959.82  105.12
 4959.91  105.09 4975.71  100.26 4993.41   95.24 4996.71   94.22 4998.21   93.44
 5005.11   94.48 5006.51   95.21 5016.61   98.74 5035.41  104.81  5036.3   105.1
 5036.41  105.13 5039.81  106.23 5092.41  106.53  5093.6  106.53 5149.51  106.67
 5207.31     107 5231.61  106.61  5342.9  106.38  5372.9  106.21  5382.9  106.59
  5437.9  106.08  5468.2  106.35  5523.2  105.41  5573.2  106.37  5648.2   107.8
BR U #Mann= 5
  4053.9      .2  4317.1     .07 4954.01     .04 5039.81     .07  5093.6     .12
BR U Banks=4954.01,5039.81
BR D #Sta/Elev= 40
  4053.9  108.68  4248.9  108.39  4283.9  107.27  4317.1  107.37  4318.9  107.38
  4333.9  107.87  4693.1  107.33  4728.1  106.77 4731.91   106.8 4791.21  107.01
 4853.31  107.44 4914.61  107.32 4954.01   106.9 4957.81  105.74 4959.82  105.12
 4959.91  105.09 4975.71  100.26 4993.41   95.24 4996.71   94.22 4998.21   93.44
 5005.11   94.48 5006.51   95.21 5016.61   98.74 5035.41  104.81  5036.3   105.1
 5036.41  105.13 5039.81  106.23 5092.41  106.53  5093.6  106.53 5149.51  106.67
 5207.31     107 5231.61  106.61  5342.9  106.38  5372.9  106.21  5382.9  106.59
  5437.9  106.08  5468.2  106.35  5523.2  105.41  5573.2  106.37  5648.2   107.8
BR D #Mann= 5
  4053.9      .2  4317.1     .07 4954.01     .04 5039.81     .07  5093.6     .12
BR D Banks=4954.01,5039.81
BC Design=,, 0 ,, 0 ,,,,,,