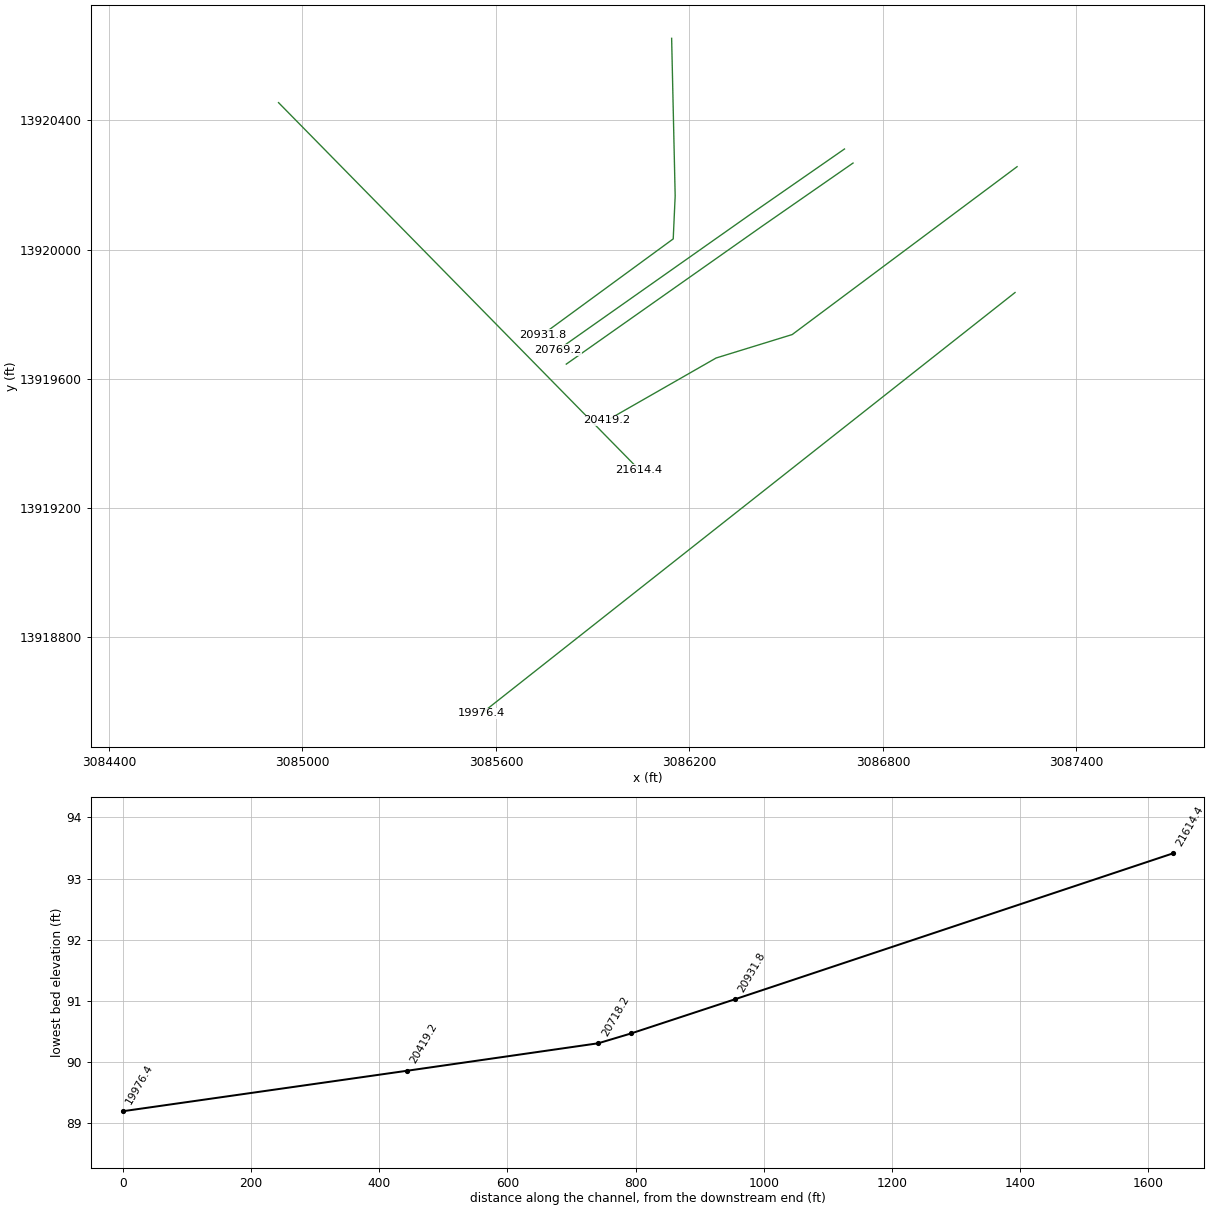
HEC-RAS study P145-00-00.PRJ: P145-00-00

--- P145-00-00.g01 (geometry) --- (continued)

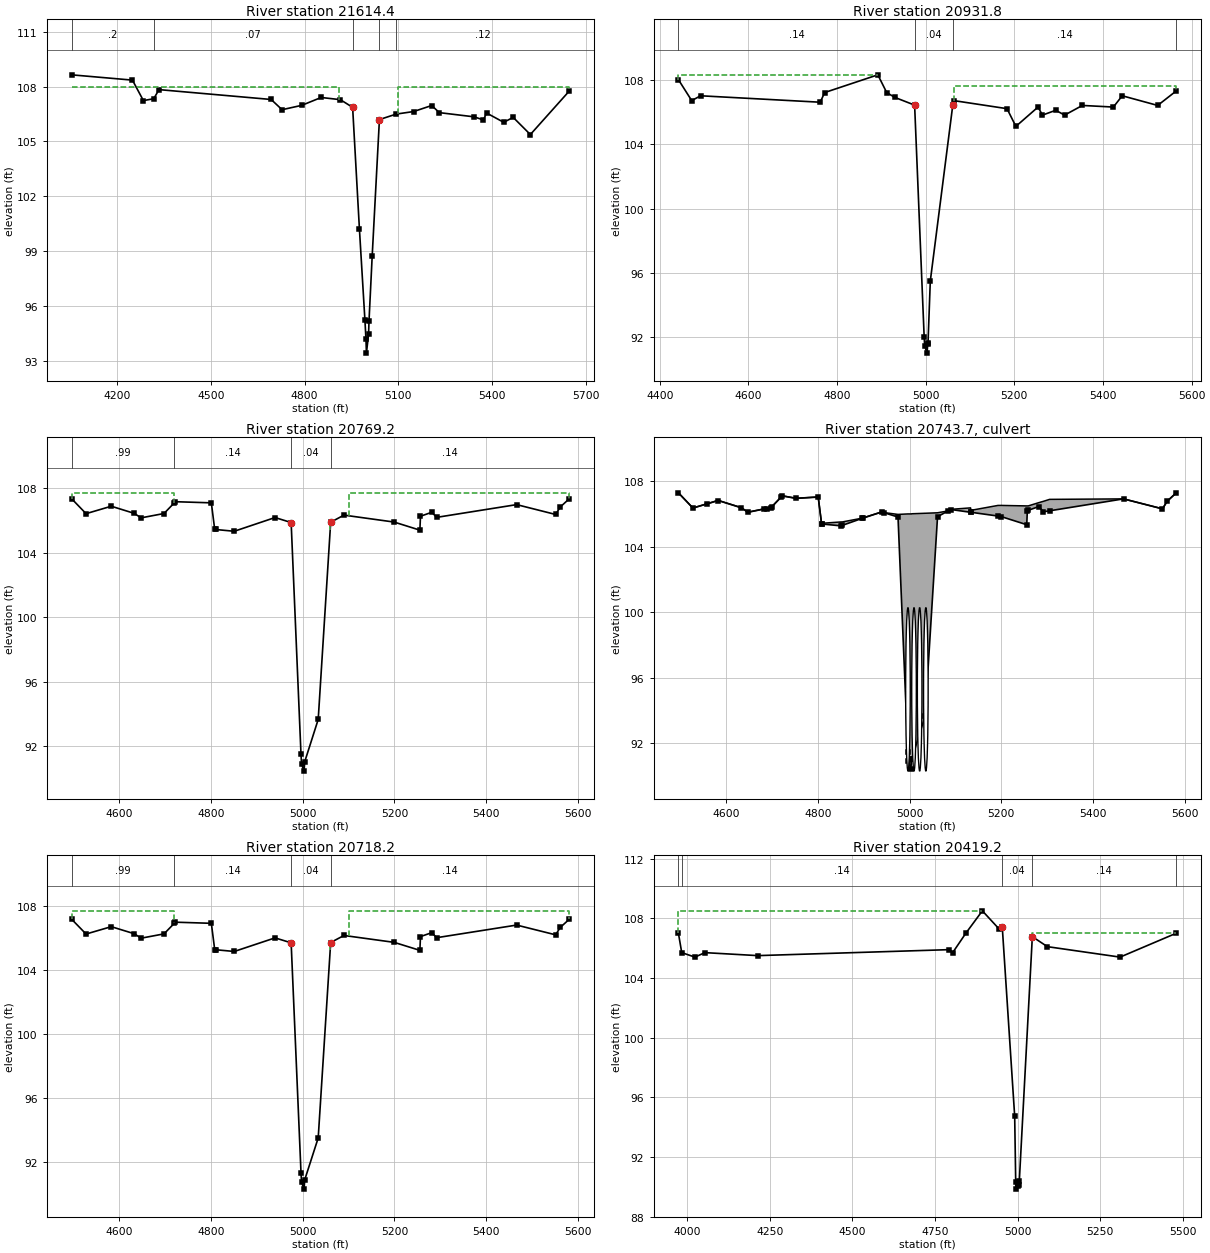
Type RM Length L Ch R = 1 ,21614.4 ,682.6,682.6,682.6
BEGIN DESCRIPTION:
Downstream Section of Bridge/Culvert/Weir
END DESCRIPTION:
XS GIS Cut Line= 2
      3084926.19     13920454.97      3086044.03     13919318.21
#Sta/Elev= 30
  4053.9  108.65  4248.9  108.36  4283.9  107.24  4317.1  107.34  4333.9  107.84
  4693.1   107.3  4728.1  106.74 4791.21  106.98 4853.31  107.41 4914.61  107.29
 4954.01  106.87 4975.71  100.23 4993.41   95.21 4996.71   94.19 4998.21   93.41
 5005.11   94.45 5006.51   95.18 5016.61   98.71 5039.81   106.2  5093.6   106.5
 5149.51  106.64 5207.31  106.97 5231.61  106.58  5342.9  106.35  5372.9  106.18
  5382.9  106.56  5437.9  106.05  5468.2  106.32  5523.2  105.38  5648.2  107.77
#Mann= 5 , 1 , 0
  4053.9      .2       0  4317.1     .07       0 4954.01     .04       0
 5039.81     .07       0  5093.6     .12       0
#XS Ineff= 2 , 0
       0    4911     108    5100       0     108
Permanent Ineff=
       F       F
Bank Sta=4954.01,5039.81
XS Rating Curve= 0
Exp/Cntr=.5,.3

Type RM Length L Ch R = 1 ,20931.8 ,417.7,162.6,73.4
BEGIN DESCRIPTION:
Cross Section 20931.8-Interpolated
END DESCRIPTION:
XS GIS Cut Line= 4
      3086144.96     13920654.12      3086155.93     13920165.96
      3086149.89     13920032.93      3085744.76     13919736.65
#Sta/Elev= 28
  4441.9     108  4471.9   106.7  4491.9     107  4761.9   106.6  4771.9   107.2
  4891.9   108.3  4911.9   107.2  4930.2   106.9  4974.9  106.42  4996.4   92.06
  4997.6   91.48  5002.9   91.03  5004.6   91.62  5005.1   91.65  5010.3   95.51
  5061.1  106.44  5063.4   106.7  5183.4   106.2  5203.4   105.1  5253.4   106.3
  5263.4   105.8  5293.4   106.1  5313.4   105.8  5353.4   106.4  5423.4   106.3
  5443.4     107  5523.4   106.4  5565.3   107.3
#Mann= 4 , 1 , 0
  4441.9     .14       0  4974.9     .04       0  5061.1     .14       0
  5565.3      .2       0
#XS Ineff= 2 , 0
       0  4891.9   108.3  5063.4       0   107.6
Permanent Ineff=
       F       F
Bank Sta=4974.9,5061.1
XS Rating Curve= 0
Exp/Cntr=.5,.3

Type RM Length L Ch R = 1 ,20769.2 ,51,51,51
BEGIN DESCRIPTION:
Upstream Section of Bridge/Culvert/Weir
END DESCRIPTION:
XS GIS Cut Line= 3
      3086680.89     13920311.39      3086399.31     13920116.06
      3085791.77     13919688.67
#Sta/Elev= 30
  4496.1  107.34  4527.7  106.41  4582.7  106.87  4632.7  106.43  4647.7  106.15
  4697.7  106.42  4719.8  107.07  4722.7  107.15  4800.9  107.08  4808.2  105.44
  4810.1  105.43  4850.8  105.32  4939.8  106.17  4974.9  105.86  4996.4    91.5
  4997.6   90.92  5002.9   90.47  5004.6   91.06  5033.9   93.67  5061.1  105.88
  5090.1  106.32  5199.5  105.89  5255.6  105.39  5256.9  106.25  5281.9   106.5
  5291.9  106.18  5466.6  106.97  5551.6  106.36  5561.6  106.82  5581.6  107.34
#Mann= 4 , 1 , 0
  4496.1     .99       0  4719.8     .14       0  4974.9     .04       0
  5061.1     .14       0
#XS Ineff= 4 ,-1
    4494    4720   107.7    4974    4975   105.8    5060    5061   105.8
    5100    5581   107.7
Permanent Ineff=
       F       F       F       F
Bank Sta=4974.9,5061.1
XS Rating Curve= 0
Exp/Cntr=.5,.3

Type RM Length L Ch R = 2 ,20743.7 ,,,
BEGIN DESCRIPTION:
ACCESS ROAD 2
Structure ID: P45-8
END DESCRIPTION:
Bridge Culvert--1,0,-1,-1, 0
Deck Dist Width WeirC Skew NumUp NumDn MinLoCord MaxHiCord MaxSubmerge Is_Ogee
10,31,3,0, 46, 46, , , .95, 0, 1,1,,
  4496.1  4527.7  4559.3  4582.7  4632.7  4647.7  4682.7  4689.3  4697.7  4699.3
  4719.8  4722.7  4752.7  4800.9  4808.2  4810.1  4850.8  4853.5  4896.8  4897.9
  4939.8    4945  4974.9  4996.4  4997.6  5002.9  5004.6  5005.1  5033.9  5061.1
  5083.2  5090.1  5133.1    5134  5192.9  5199.5  5255.6  5256.9  5258.9  5281.9
  5291.9  5305.4  5466.6  5551.6  5561.6  5581.6
   107.3  106.37  106.64  106.84   106.4  106.12  106.32  106.35  106.39  106.44
  107.04  107.12  106.97  107.05  105.44  105.44  105.52  105.52  105.75  105.76
  106.14  106.09  105.98  106.01  106.01  106.01  106.01  106.02  106.05  106.08
  106.19  106.29  106.38  106.23  106.53  106.53   106.5   106.5   106.5   106.7
  106.78   106.9  106.93  106.32  106.78   107.3
   107.3  106.37  106.63  106.83  106.39  106.11  106.31  106.34  106.38  106.43
  107.03  107.11  106.96  107.04   105.4  105.39  105.28  105.31  105.74  105.75
  106.13  106.08  105.82   91.46   90.88   90.43   91.02   91.05   93.63  105.84
  106.18  106.28  106.11  106.11  105.88  105.85  105.35  106.21  106.23  106.46
  106.14   106.2  106.93  106.32  106.78   107.3
  4496.1  4527.7  4559.3  4582.7  4632.7  4647.7  4682.7  4689.3  4697.7  4699.3
  4719.8  4722.7  4752.7  4800.9  4808.2  4810.1  4850.8  4853.5  4896.8  4897.9
  4939.8    4945  4974.9  4996.4  4997.6  5002.9  5004.6  5005.1  5033.9  5061.1
  5083.2  5090.1  5133.1    5134  5192.9  5199.5  5255.6  5256.9  5258.9  5281.9
  5291.9  5305.4  5466.6  5551.6  5561.6  5581.6
   107.3  106.37  106.64  106.84   106.4  106.12  106.32  106.35  106.39  106.44
  107.04  107.12  106.97  107.05  105.44  105.44  105.52  105.52  105.75  105.76
  106.14  106.09  105.98  106.01  106.01  106.01  106.01  106.02  106.05  106.08
  106.19  106.29  106.38  106.23  106.53  106.53   106.5   106.5   106.5   106.7
  106.78   106.9  106.93  106.32  106.78   107.3
   107.2  106.27  106.53  106.73  106.29  106.01  106.21  106.24  106.28  106.33
  106.93  107.01  106.86  106.94   105.3  105.29  105.18  105.21  105.64  105.65
  106.03  105.98  105.72   91.36   90.78   90.33   90.92   90.95   93.53  105.74
  106.08  106.18  106.01  106.01  105.78  105.75  105.25  106.11  106.13  106.36
  106.04   106.1  106.83  106.22  106.68   107.2
BR Coef= 1 , 0 , 0 ,1.25, 0 ,,,.8,-1,2,0,
WSPro=,,,, 1 ,,,, 0 ,,,, 0 ,,,,-1 ,-1 ,-1 , 0 , 0 , 0 , 0 , 0
Culvert=1,10,,31,.024,.9,1,1,3,90.28,4996.6,90.14,4996.6,Culvert #1  , 0 ,10
Culvert Bottom n=.024
Culvert=1,10,,31,.024,.9,1,1,3,90.28,5009.8,90.14,5009.8,Culvert #2  , 0 ,10
Culvert Bottom n=.024
Culvert=1,10,,31,.024,.9,1,1,3,90.28,5022.1,90.14,5022.1,Culvert #3  , 0 ,10
Culvert Bottom n=.024
Culvert=1,10,,31,.024,.9,1,1,3,90.28,5035.6,90.14,5035.6,Culvert #4  , 0 ,10
Culvert Bottom n=.024
BR U #Sta/Elev= 46
  4496.1   107.3  4527.7  106.37  4559.3  106.63  4582.7  106.83  4632.7  106.39
  4647.7  106.11  4682.7  106.31  4689.3  106.34  4697.7  106.38  4699.3  106.43
  4719.8  107.03  4722.7  107.11  4752.7  106.96  4800.9  107.04  4808.2   105.4
  4810.1  105.39  4850.8  105.28  4853.5  105.31  4896.8  105.74  4897.9  105.75
  4939.8  106.13    4945  106.08  4974.9  105.82  4996.4   91.46  4997.6   90.88
  5002.9   90.43  5004.6   91.02  5005.1   91.05  5033.9   93.63  5061.1  105.84
  5083.2  106.18  5090.1  106.28  5133.1  106.11    5134  106.11  5192.9  105.88
  5199.5  105.85  5255.6  105.35  5256.9  106.21  5258.9  106.23  5281.9  106.46
  5291.9  106.14  5305.4   106.2  5466.6  106.93  5551.6  106.32  5561.6  106.78
  5581.6   107.3
BR U #Mann= 4
  4496.1     .99  4719.8     .14  4974.9     .04  5061.1     .14
BR U Banks=4974.9,5061.1
BR D #Sta/Elev= 46
  4496.1   107.2  4527.7  106.27  4559.3  106.53  4582.7  106.73  4632.7  106.29
  4647.7  106.01  4682.7  106.21  4689.3  106.24  4697.7  106.28  4699.3  106.33
  4719.8  106.93  4722.7  107.01  4752.7  106.86  4800.9  106.94  4808.2   105.3
  4810.1  105.29  4850.8  105.18  4853.5  105.21  4896.8  105.64  4897.9  105.65
  4939.8  106.03    4945  105.98  4974.9  105.72  4996.4   91.36  4997.6   90.78
  5002.9   90.33  5004.6   90.92  5005.1   90.95  5033.9   93.53  5061.1  105.74
  5083.2  106.08  5090.1  106.18  5133.1  106.01    5134  106.01  5192.9  105.78
  5199.5  105.75  5255.6  105.25  5256.9  106.11  5258.9  106.13  5281.9  106.36
  5291.9  106.04  5305.4   106.1  5466.6  106.83  5551.6  106.22  5561.6  106.68
  5581.6   107.2
BR D #Mann= 4
  4496.1     .99  4719.8     .14  4974.9     .04  5061.1     .14
BR D Banks=4974.9,5061.1
BC Design=,, 0 ,, 0 ,,,,,,

Type RM Length L Ch R = 1 ,20718.2 ,299,299,299
BEGIN DESCRIPTION:
Downstream Section of Bridge/Culvert/Weir
END DESCRIPTION:
XS GIS Cut Line= 3
      3086707.45     13920267.86      3086425.87     13920072.52
      3085818.34     13919645.14
#Sta/Elev= 30
  4496.1  107.18  4527.7  106.25  4582.7  106.71  4632.7  106.27  4647.7  105.99
  4697.7  106.26  4719.8  106.91  4722.7  106.99  4800.9  106.92  4808.2  105.28
  4810.1  105.27  4850.8  105.16  4939.8  106.01  4974.9   105.7  4996.4   91.34
  4997.6   90.76  5002.9   90.31  5004.6    90.9  5033.9   93.51  5061.1  105.72
  5090.1  106.16  5199.5  105.73  5255.6  105.23  5256.9  106.09  5281.9  106.34
  5291.9  106.02  5466.6  106.81  5551.6   106.2  5561.6  106.66  5581.6  107.18
#Mann= 4 , 1 , 0
  4496.1     .99       0  4719.8     .14       0  4974.9     .04       0
  5061.1     .14       0
#XS Ineff= 4 ,-1
    4494    4720   107.7    4974    4975   105.8    5060    5061   105.8
    5100    5581   107.7
Permanent Ineff=
       F       F       F       F
Bank Sta=4974.9,5061.1
XS Rating Curve= 0
Exp/Cntr=.5,.3

Type RM Length L Ch R = 1 ,20419.2 ,539,442.8,438.9
BEGIN DESCRIPTION:
Cross Section 20419.2-Interpolated
END DESCRIPTION:
XS GIS Cut Line= 4
      3087216.05     13920256.58      3086518.73     13919736.65
      3086282.91     13919664.09       3085944.3     13919470.59
#Sta/Elev= 21
  3973.8     107  3983.8   105.7  4023.8   105.4  4053.8   105.7  4213.8   105.5
  4793.8   105.9  4803.8   105.7  4843.6     107  4893.6   108.5  4943.6   107.3
 4953.94  107.39 4991.44   94.74 4994.54   90.35 4994.94   89.86 5002.44   90.04
 5003.64   90.15 5005.44    90.4 5044.84  106.77  5090.4   106.1  5310.4   105.4
  5480.4     107
#Mann= 5 , 1 , 0
  3973.8      .2       0  3983.8     .14       0 4953.94     .04       0
 5044.84     .14       0  5480.4      .2       0
#XS Ineff= 2 , 0
       0  4893.6   108.5 5044.84       0     107
Permanent Ineff=
       F       F
Bank Sta=4953.94,5044.84
XS Rating Curve= 0
Exp/Cntr=.5,.3

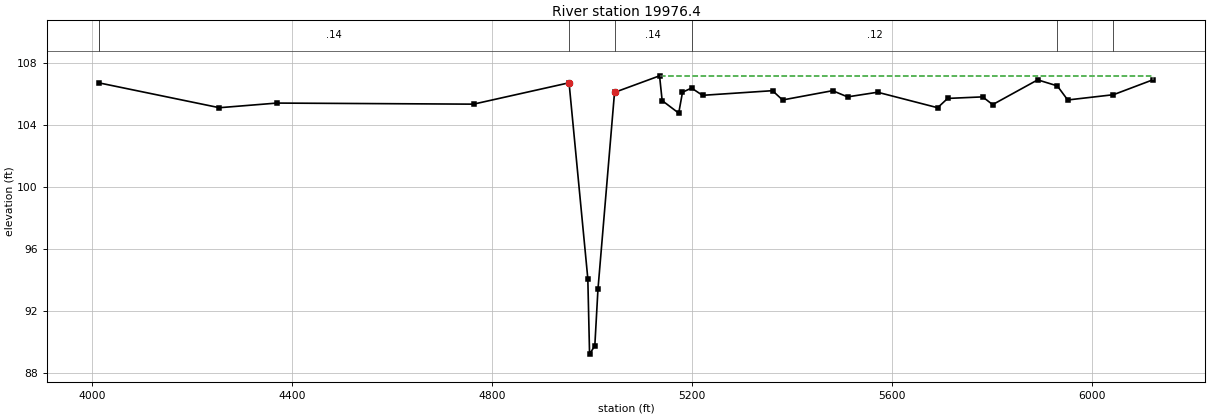
Type RM Length L Ch R = 1 ,19976.4 ,23,23,23
BEGIN DESCRIPTION:
Upstream Section of Bridge/Culvert/Weir
END DESCRIPTION:
XS GIS Cut Line= 2
      3087209.66     13919866.81      3085555.84     13918563.41
#Sta/Elev= 30
    4015  106.72    4255  105.12  4369.8  105.42 4762.94  105.35 4953.94  106.73
 4991.44   94.08 4994.94    89.2 5005.44   89.74 5011.74    93.4 5044.84  106.11
 5134.84  107.18 5140.04  105.58 5173.14  104.77  5180.7  106.12  5198.8  106.39
  5220.7  105.92  5360.7  106.22  5380.7  105.62  5480.7  106.22  5510.7  105.82
  5570.7  106.12  5690.7  105.12  5710.7  105.72  5780.7  105.82  5800.7  105.32
  5890.7  106.92  5929.9  106.53  5950.7  105.62  6042.1  105.96  6120.7  106.92
#Mann= 7 , 1 , 0
    4015      .2       0    4015     .14       0 4953.94     .04       0
 5044.84     .14       0  5198.8     .12       0  5929.9      .1       0
  6042.1     .12       0
#XS Ineff= 2 , 0
       0 4953.94  106.71 5134.84       0  107.16
Permanent Ineff=
       F       F
Bank Sta=4953.94,5044.84
XS Rating Curve= 0
Exp/Cntr=.5,.3