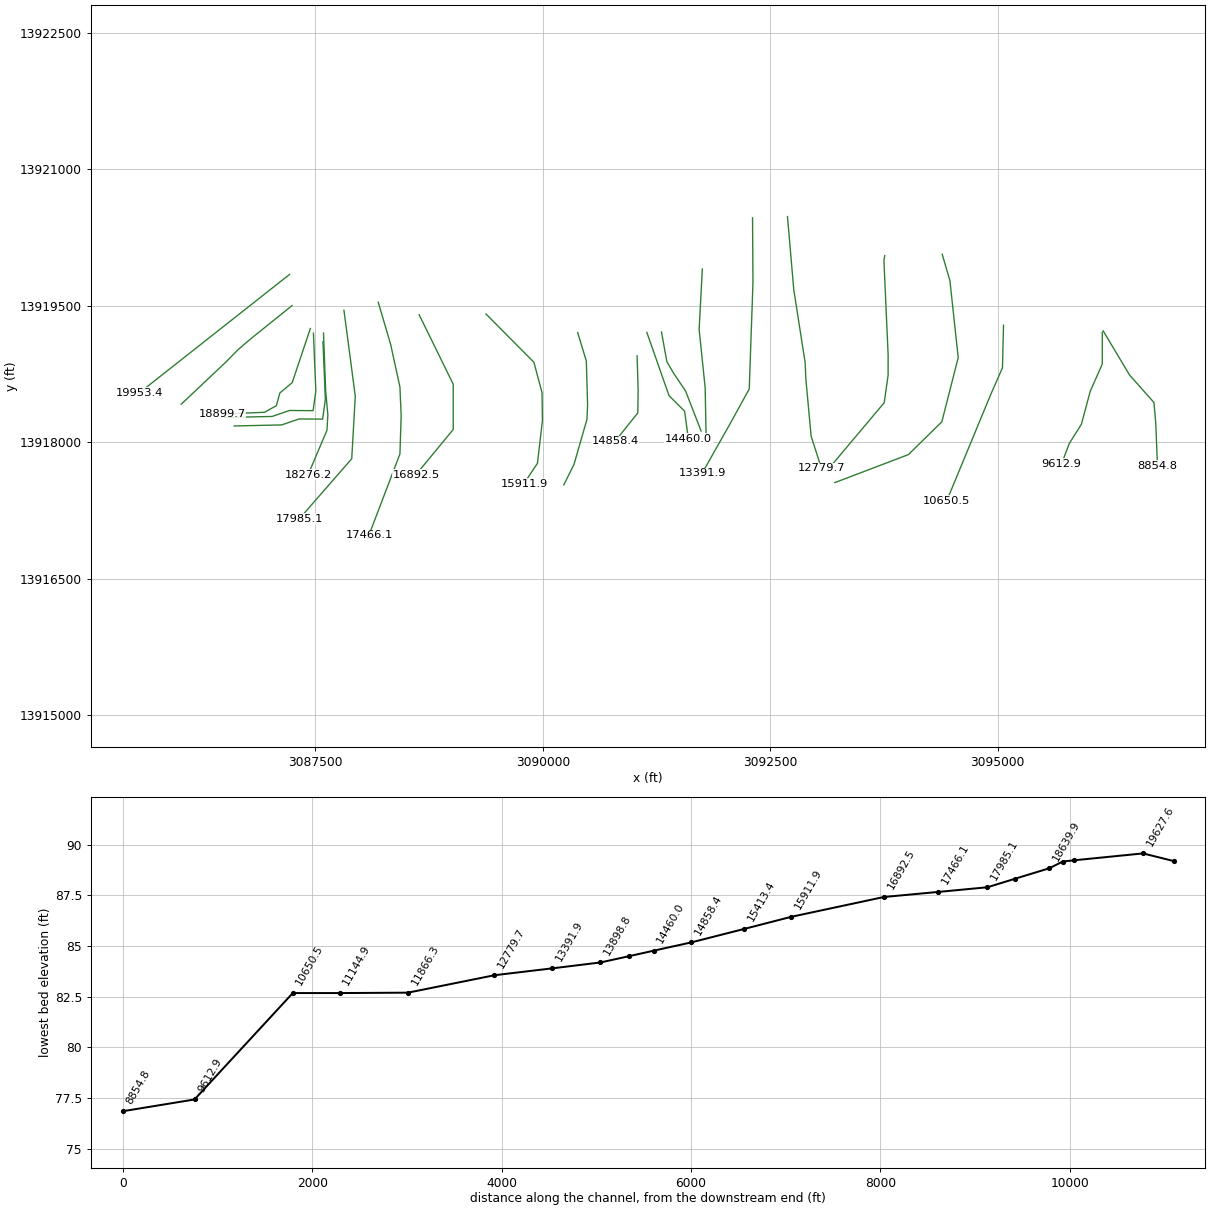
HEC-RAS study P145-00-00.PRJ: P145-00-00

--- P145-00-00.g01 (geometry) --- (continued)

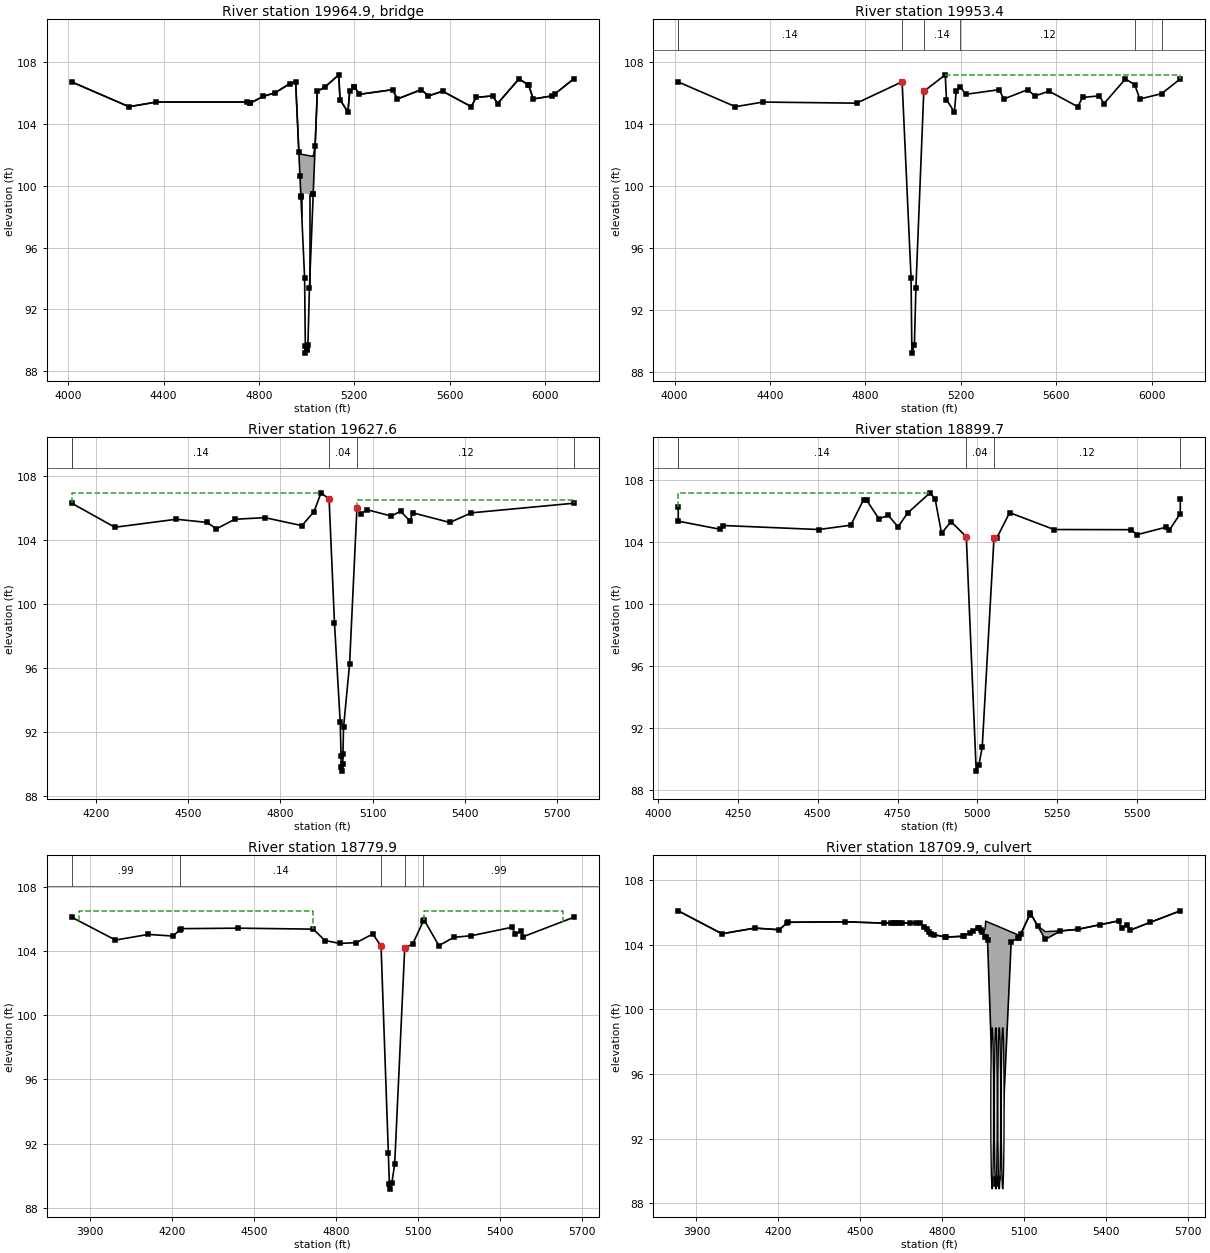
Type RM Length L Ch R = 3 ,19964.9 ,,,
BEGIN DESCRIPTION:
30" PIPELINE
END DESCRIPTION:
Bridge Culvert--1,0,-1,-1, 0
Deck Dist Width WeirC Skew NumUp NumDn MinLoCord MaxHiCord MaxSubmerge Is_Ogee
10,3,2.6,0, 49, 49, , , .95, 0, 1,1,,
    4015    4255  4369.8  4750.8 4761.74 4762.94 4816.84 4869.14 4928.44 4953.94
 4967.44 4971.94 4975.85 4975.94 4991.44 4994.54 4994.94 5002.44 5003.64 5005.44
 5011.74 5027.53 5027.64 5035.64 5044.84 5078.14 5134.84 5140.04 5173.14  5180.7
  5198.8  5200.7  5220.7  5360.7  5380.7  5480.7  5510.7  5570.7  5690.7  5710.7
  5780.7  5800.7  5890.7  5929.9  5930.7  5950.7  6030.7  6042.1  6120.7
   106.7   105.1   105.4   105.4  105.34  105.33  105.76  106.01  106.58  106.71
  102.17  102.04  102.03  102.03  101.99  101.98  101.98  101.96  101.96  101.95
  101.93  101.89  101.89  102.57  106.09  106.39  107.16  105.56  104.75   106.1
  106.37   106.4   105.9   106.2   105.6   106.2   105.8   106.1   105.1   105.7
   105.8   105.3   106.9  106.51   106.5   105.6   105.8  105.94   106.9
   106.7   105.1   105.4   105.4  105.34  105.33  105.76  106.01  106.58  106.71
  102.16  100.64   99.32   99.53   99.49   99.48   99.48   99.46   99.46   99.45
   99.43   99.44   99.49  102.56  106.09  106.39  107.16  105.56  104.75   106.1
  106.37   106.4   105.9   106.2   105.6   106.2   105.8   106.1   105.1   105.7
   105.8   105.3   106.9  106.51   106.5   105.6   105.8  105.94   106.9
    4015    4255  4369.8  4750.8 4761.74 4762.94 4816.84 4869.14 4928.44 4953.94
 4967.44 4971.94 4975.85 4975.94 4991.44 4994.54 4994.94 5002.44 5003.64 5005.44
 5011.74 5027.53 5027.64 5035.64 5044.84 5078.14 5134.84 5140.04 5173.14  5180.7
  5198.8  5200.7  5220.7  5360.7  5380.7  5480.7  5510.7  5570.7  5690.7  5710.7
  5780.7  5800.7  5890.7  5929.9  5930.7  5950.7  6030.7  6042.1  6120.7
   106.7   105.1   105.4   105.4  105.34  105.33  105.76  106.01  106.58  106.71
  102.17  102.04  102.03  102.03  101.99  101.98  101.98  101.96  101.96  101.95
  101.93  101.89  101.89  102.57  106.09  106.39  107.16  105.56  104.75   106.1
  106.37   106.4   105.9   106.2   105.6   106.2   105.8   106.1   105.1   105.7
   105.8   105.3   106.9  106.51   106.5   105.6   105.8  105.94   106.9
   106.7   105.1   105.4   105.4  105.34  105.33  105.76  106.01  106.58  106.71
  102.16  100.64   99.32   99.53   99.49   99.48   99.48   99.46   99.46   99.45
   99.43   99.44   99.49  102.56  106.09  106.39  107.16  105.56  104.75   106.1
  106.37   106.4   105.9   106.2   105.6   106.2   105.8   106.1   105.1   105.7
   105.8   105.3   106.9  106.51   106.5   105.6   105.8  105.94   106.9
Pier Skew, UpSta & Num, DnSta & Num=  ,4979.9, 2 ,4979.9, 2 , 0 , 0 , 0 ,,
       1       1
   96.77  100.52
       1       1
   96.77  100.52
Pier Skew, UpSta & Num, DnSta & Num=  ,5011.7, 2 ,5011.7, 2 , 0 , 0 , 0 ,,
       1       1
   92.09  100.43
       1       1
   92.09  100.43
BR Coef= 1 , 1 , 0 ,1.25, 0 ,,,.8,0,2,0,
WSPro=,,,, 1 ,,,, 0 ,,,, 0 ,,,,-1 ,-1 ,-1 , 0 , 0 , 0 , 0 , 0
BR U #Sta/Elev= 49
    4015   106.7    4255   105.1  4369.8   105.4  4750.8   105.4 4761.74  105.34
 4762.94  105.33 4816.84  105.76 4869.14  106.01 4928.44  106.58 4953.94  106.71
 4967.44  102.16 4971.94  100.64 4975.85   99.32 4975.94   99.29 4991.44   94.06
 4994.54   89.67 4994.94   89.18 5002.44   89.36 5003.64   89.47 5005.44   89.72
 5011.74   93.38 5027.53   99.44 5027.64   99.49 5035.64  102.56 5044.84  106.09
 5078.14  106.39 5134.84  107.16 5140.04  105.56 5173.14  104.75  5180.7   106.1
  5198.8  106.37  5200.7   106.4  5220.7   105.9  5360.7   106.2  5380.7   105.6
  5480.7   106.2  5510.7   105.8  5570.7   106.1  5690.7   105.1  5710.7   105.7
  5780.7   105.8  5800.7   105.3  5890.7   106.9  5929.9  106.51  5930.7   106.5
  5950.7   105.6  6030.7   105.8  6042.1  105.94  6120.7   106.9
BR U #Mann= 7
    4015      .2    4015     .14 4953.94     .04 5044.84     .14  5198.8     .12
  5929.9      .1  6042.1     .12
BR U Banks=4953.94,5044.84
BR D #Sta/Elev= 49
    4015   106.7    4255   105.1  4369.8   105.4  4750.8   105.4 4761.74  105.34
 4762.94  105.33 4816.84  105.76 4869.14  106.01 4928.44  106.58 4953.94  106.71
 4967.44  102.16 4971.94  100.64 4975.85   99.32 4975.94   99.29 4991.44   94.06
 4994.54   89.67 4994.94   89.18 5002.44   89.36 5003.64   89.47 5005.44   89.72
 5011.74   93.38 5027.53   99.44 5027.64   99.49 5035.64  102.56 5044.84  106.09
 5078.14  106.39 5134.84  107.16 5140.04  105.56 5173.14  104.75  5180.7   106.1
  5198.8  106.37  5200.7   106.4  5220.7   105.9  5360.7   106.2  5380.7   105.6
  5480.7   106.2  5510.7   105.8  5570.7   106.1  5690.7   105.1  5710.7   105.7
  5780.7   105.8  5800.7   105.3  5890.7   106.9  5929.9  106.51  5930.7   106.5
  5950.7   105.6  6030.7   105.8  6042.1  105.94  6120.7   106.9
BR D #Mann= 7
    4015      .2    4015     .14 4953.94     .04 5044.84     .14  5198.8     .12
  5929.9      .1  6042.1     .12
BR D Banks=4953.94,5044.84
BC Design=,, 0 ,, 0 ,,,,,,

Type RM Length L Ch R = 1 ,19953.4 ,325.8,325.8,325.8
BEGIN DESCRIPTION:
Downstream Section of Bridge/Culvert/Weir
END DESCRIPTION:
XS GIS Cut Line= 2
      3087216.34      13919844.8      3085562.52      13918541.4
#Sta/Elev= 30
    4015  106.71    4255  105.11  4369.8  105.41 4762.94  105.34 4953.94  106.72
 4991.44   94.07 4994.94   89.19 5005.44   89.73 5011.74   93.39 5044.84   106.1
 5134.84  107.17 5140.04  105.57 5173.14  104.76  5180.7  106.11  5198.8  106.38
  5220.7  105.91  5360.7  106.21  5380.7  105.61  5480.7  106.21  5510.7  105.81
  5570.7  106.11  5690.7  105.11  5710.7  105.71  5780.7  105.81  5800.7  105.31
  5890.7  106.91  5929.9  106.52  5950.7  105.61  6042.1  105.95  6120.7  106.91
#Mann= 7 , 1 , 0
    4015      .2       0    4015     .14       0 4953.94     .04       0
 5044.84     .14       0  5198.8     .12       0  5929.9      .1       0
  6042.1     .12       0
#XS Ineff= 2 , 0
       0 4953.94  106.71 5134.84       0  107.16
Permanent Ineff=
       F       F
Bank Sta=4953.94,5044.84
XS Rating Curve= 0
Exp/Cntr=.5,.3

Type RM Length L Ch R = 1 ,19627.6 ,708.1,727.9,716.9
BEGIN DESCRIPTION:
Cross Section 19627.6
END DESCRIPTION:
XS GIS Cut Line= 6
      3087243.46     13919502.24      3086822.38     13919163.45
      3086754.62     13919107.79      3086650.56     13919018.25
      3086515.04     13918880.31       3086025.5      13918418.3
#Sta/Elev= 30
  4121.8   106.3  4261.8   104.8  4461.8   105.3  4561.8   105.1  4591.8   104.7
  4651.8   105.3  4749.9   105.4  4869.9   104.9  4909.3  105.78    4932  106.95
  4958.2  106.56  4975.6   98.84  4994.4   92.61    4997   90.52  4997.4   89.84
  5000.4   89.57  5002.9   90.01  5003.1   90.61  5005.2   92.31  5024.8   96.27
  5048.7  106.02    5062  105.62  5080.6   105.9  5160.6   105.5  5190.6   105.8
  5220.6   105.2  5230.6   105.7  5350.6   105.1  5420.6   105.7  5753.7   106.3
#Mann= 5 , 1 , 0
  4121.8      .2       0  4121.8     .14       0  4958.2     .04       0
  5048.7     .12       0  5753.7      .2       0
#XS Ineff= 2 , 0
       0    4932  106.95  5048.7       0   106.5
Permanent Ineff=
       F       F
Bank Sta=4958.2,5048.7
XS Rating Curve= 0
Exp/Cntr=.3,.1

Type RM Length L Ch R = 1 ,18899.7 ,124.6,119.8,85.5
BEGIN DESCRIPTION:
Cross Section 18899.7-Interpolated
END DESCRIPTION:
XS GIS Cut Line= 6
      3087445.09     13919250.46      3087245.44     13918655.23
      3087110.09     13918542.43      3087071.39     13918402.15
      3086940.79     13918329.59       3086476.4     13918310.24
#Sta/Elev= 30
  4063.5   106.3  4063.6  105.37  4193.6  104.85  4203.6  105.09  4503.6  104.83
  4603.6  105.11  4643.6  106.76  4653.6  106.71  4691.4  105.53  4721.4  105.74
  4751.4     105  4781.4  105.89  4851.4   107.2  4867.6  106.81  4887.6  104.59
  4917.6  105.34  4965.2  104.36  4996.2   89.23  5004.6   89.62    5015   90.77
  5051.8  104.26  5060.8  104.29  5100.8  105.92  5240.2  104.83  5480.2  104.82
  5500.2   104.5  5590.2  104.98  5600.2  104.77    5635  105.86  5635.1   106.8
#Mann= 5 , 1 , 0
  4063.5      .2       0  4063.6     .14       0  4965.2     .04       0
  5051.8     .12       0    5635      .2       0
#XS Ineff= 2 , 0
       0  4851.4   107.2  5100.8       0  105.92
Permanent Ineff=
       F       F
Bank Sta=4965.2,5051.8
XS Rating Curve= 0
Exp/Cntr=.5,.3

Type RM Length L Ch R = 1 ,18779.9 ,140,140,140
BEGIN DESCRIPTION:
Upstream Section of Bridge/Culvert/Weir
END DESCRIPTION:
XS GIS Cut Line= 6
      3087478.94     13919199.04      3087505.22     13918563.75
      3087475.32     13918347.62      3087216.02     13918349.21
      3087024.72     13918283.78      3086503.57     13918272.14
#Sta/Elev= 30
  3833.5   106.1  3993.5  104.68  4113.5  105.03  4203.5  104.93  4229.8  105.33
  4233.5  105.39  4443.5  105.42  4717.2  105.36  4759.8  104.65  4814.4  104.47
    4875  104.52    4935  105.06  4965.2   104.3  4991.9   91.41  4995.5   89.48
  4996.2   89.17  5004.6   89.56    5015   90.71  5051.8   104.2  5080.5  104.42
  5119.8  105.86  5122.2  105.95  5176.7  104.33  5231.5  104.85  5295.5  104.95
  5445.5  105.48  5455.5  105.05  5475.5  105.23  5485.5  104.89  5670.6   106.1
#Mann= 5 , 1 , 0
  3833.5     .99       0  4229.8     .14       0  4965.2     .04       0
  5051.8     .12       0  5119.8     .99       0
#XS Ineff= 4 ,-1
    3860    4717   106.5    4964    4965   104.3    5052    5053   104.2
  5122.1    5630   106.5
Permanent Ineff=
       F       F       F       F
Bank Sta=4965.2,5051.8
XS Rating Curve= 0
Exp/Cntr=.5,.3

Type RM Length L Ch R = 2 ,18709.9 ,,,
BEGIN DESCRIPTION:
ACCESS ROAD 1
Structure ID: P45-7
END DESCRIPTION:
Bridge Culvert--1,0,-1,-1, 0
Deck Dist Width WeirC Skew NumUp NumDn MinLoCord MaxHiCord MaxSubmerge Is_Ogee
10,120,3,0, 58, 58, , , .95, 0, 1,1,,
  3833.5  3993.5  4113.5  4203.5  4229.8  4233.5  4443.5  4586.8  4611.9  4621.9
  4631.9  4641.9  4651.9  4681.9  4701.9  4717.2  4731.9  4741.9  4750.6  4759.8
  4770.6  4810.6  4814.4    4875  4880.6  4900.6  4910.6  4930.6    4935  4940.6
  4946.8  4956.8  4958.4  4965.2  4991.9  4995.5  4996.2  4999.2  5001.2  5004.6
    5015  5051.8  5076.3  5080.5    5087  5119.8  5122.2  5149.3  5176.7  5231.5
  5295.5  5375.3  5445.5  5455.5  5475.5  5485.5  5560.7  5670.6
   106.1  104.68  105.03  104.93  105.33  105.39  105.42  105.34  105.35  105.36
  105.36  105.36  105.36  105.36  105.37  105.37  105.12  104.96  104.81  104.66
  104.62  104.49  104.48  104.53  104.58  104.76  104.85  105.03  105.07  104.93
  104.77     105  105.46  105.41  105.22   105.2  105.19  105.17  105.16  105.13
  105.06  104.79  104.62  104.53  104.67  105.87  105.96  105.15  104.81  104.86
  104.96  105.24  105.48  105.05  105.23  104.89  105.39   106.1
   106.1  104.68  105.03  104.93  105.33  105.39  105.42  105.34  105.34  105.35
  105.35  105.35  105.35  105.35  105.36  105.36  105.11  104.95   104.8  104.65
  104.61  104.48  104.47  104.52  104.57  104.75  104.84  105.02  105.06  104.92
  104.76  104.51  104.47   104.3   91.41   89.48   89.17   89.28   89.38   89.56
   90.71   104.2  104.39  104.42  104.66  105.86  105.95  105.14  104.33  104.85
  104.95  105.23  105.48  105.05  105.23  104.89  105.39   106.1
  3833.5  3993.5  4113.5  4203.5  4229.8  4233.5  4443.5  4586.8  4611.9  4621.9
  4631.9  4641.9  4651.9  4681.9  4701.9  4717.2  4731.9  4741.9  4750.6  4759.8
  4770.6  4810.6  4814.4    4875  4880.6  4900.6  4910.6  4930.6    4935  4940.6
  4946.8  4956.8  4958.4  4965.2  4991.9  4995.5  4996.2  4999.2  5001.2  5004.6
    5015  5051.8  5076.3  5080.5    5087  5119.8  5122.2  5149.3  5176.7  5231.5
  5295.5  5375.3  5445.5  5455.5  5475.5  5485.5  5560.7  5670.6
   106.1  104.68  105.03  104.93  105.33  105.39  105.42  105.34  105.35  105.36
  105.36  105.36  105.36  105.36  105.37  105.37  105.12  104.96  104.81  104.66
  104.62  104.49  104.48  104.53  104.58  104.76  104.85  105.03  105.07  104.93
  104.77     105  105.46  105.41  105.22   105.2  105.19  105.17  105.16  105.13
  105.06  104.79  104.62  104.53  104.67  105.87  105.96  105.15  104.81  104.86
  104.96  105.24  105.48  105.05  105.23  104.89  105.39   106.1
  105.78  104.36  104.71  104.61  105.01  105.07   105.1  105.02  105.02  105.03
  105.03  105.03  105.03  105.03  105.04  105.04  104.79  104.63  104.48  104.33
  104.29  104.16  104.15   104.2  104.25  104.43  104.52   104.7  104.74   104.6
  104.44  104.19  104.15  103.98   91.09   89.16   88.85   88.96   89.06   89.24
   90.39  103.88  104.07   104.1  104.34  105.54  105.63  104.82  104.01  104.53
  104.63  104.91  105.16  104.73  104.91  104.57  105.07  105.78
BR Coef= 1 , 0 , 0 ,1.25, 0 ,,,.8,-1,2,0,
WSPro=,,,, 1 ,,,, 0 ,,,, 0 ,,,,-1 ,-1 ,-1 , 0 , 0 , 0 , 0 , 0
Culvert=1,10,,120,.024,.9,1,1,3,88.87,4982.2,88.74,4982.2,Culvert #1  , 0 ,10
Culvert Bottom n=.024
Culvert=1,10,,120,.024,.9,1,1,3,88.87,4995.5,88.74,4995.5,Culvert #2  , 0 ,10
Culvert Bottom n=.024
Culvert=1,10,,120,.024,.9,1,1,3,88.87,5008,88.74,5008,Culvert #3  , 0 ,10
Culvert Bottom n=.024
Culvert=1,10,,120,.024,.9,1,1,3,88.87,5020.7,88.74,5020.7,Culvert #4  , 0 ,10
Culvert Bottom n=.024
BR U #Sta/Elev= 58
  3833.5   106.1  3993.5  104.68  4113.5  105.03  4203.5  104.93  4229.8  105.33
  4233.5  105.39  4443.5  105.42  4586.8  105.34  4611.9  105.34  4621.9  105.35
  4631.9  105.35  4641.9  105.35  4651.9  105.35  4681.9  105.35  4701.9  105.36
  4717.2  105.36  4731.9  105.11  4741.9  104.95  4750.6   104.8  4759.8  104.65
  4770.6  104.61  4810.6  104.48  4814.4  104.47    4875  104.52  4880.6  104.57
  4900.6  104.75  4910.6  104.84  4930.6  105.02    4935  105.06  4940.6  104.92
  4946.8  104.76  4956.8  104.51  4958.4  104.47  4965.2   104.3  4991.9   91.41
  4995.5   89.48  4996.2   89.17  4999.2   89.28  5001.2   89.38  5004.6   89.56
    5015   90.71  5051.8   104.2  5076.3  104.39  5080.5  104.42    5087  104.66
  5119.8  105.86  5122.2  105.95  5149.3  105.14  5176.7  104.33  5231.5  104.85
  5295.5  104.95  5375.3  105.23  5445.5  105.48  5455.5  105.05  5475.5  105.23
  5485.5  104.89  5560.7  105.39  5670.6   106.1
BR U #Mann= 5
  3833.5     .99  4229.8     .14  4965.2     .04  5051.8     .12  5119.8     .99
BR U Banks=4965.2,5051.8
BR D #Sta/Elev= 58
  3833.5  105.78  3993.5  104.36  4113.5  104.71  4203.5  104.61  4229.8  105.01
  4233.5  105.07  4443.5   105.1  4586.8  105.02  4611.9  105.02  4621.9  105.03
  4631.9  105.03  4641.9  105.03  4651.9  105.03  4681.9  105.03  4701.9  105.04
  4717.2  105.04  4731.9  104.79  4741.9  104.63  4750.6  104.48  4759.8  104.33
  4770.6  104.29  4810.6  104.16  4814.4  104.15    4875   104.2  4880.6  104.25
  4900.6  104.43  4910.6  104.52  4930.6   104.7    4935  104.74  4940.6   104.6
  4946.8  104.44  4956.8  104.19  4958.4  104.15  4965.2  103.98  4991.9   91.09
  4995.5   89.16  4996.2   88.85  4999.2   88.96  5001.2   89.06  5004.6   89.24
    5015   90.39  5051.8  103.88  5076.3  104.07  5080.5   104.1    5087  104.34
  5119.8  105.54  5122.2  105.63  5149.3  104.82  5176.7  104.01  5231.5  104.53
  5295.5  104.63  5375.3  104.91  5445.5  105.16  5455.5  104.73  5475.5  104.91
  5485.5  104.57  5560.7  105.07  5670.6  105.78
BR D #Mann= 5
  3833.5     .99  4229.8     .14  4965.2     .04  5051.8     .12  5119.8     .99
BR D Banks=4965.2,5051.8
BC Design=,, 0 ,, 0 ,,,,,,

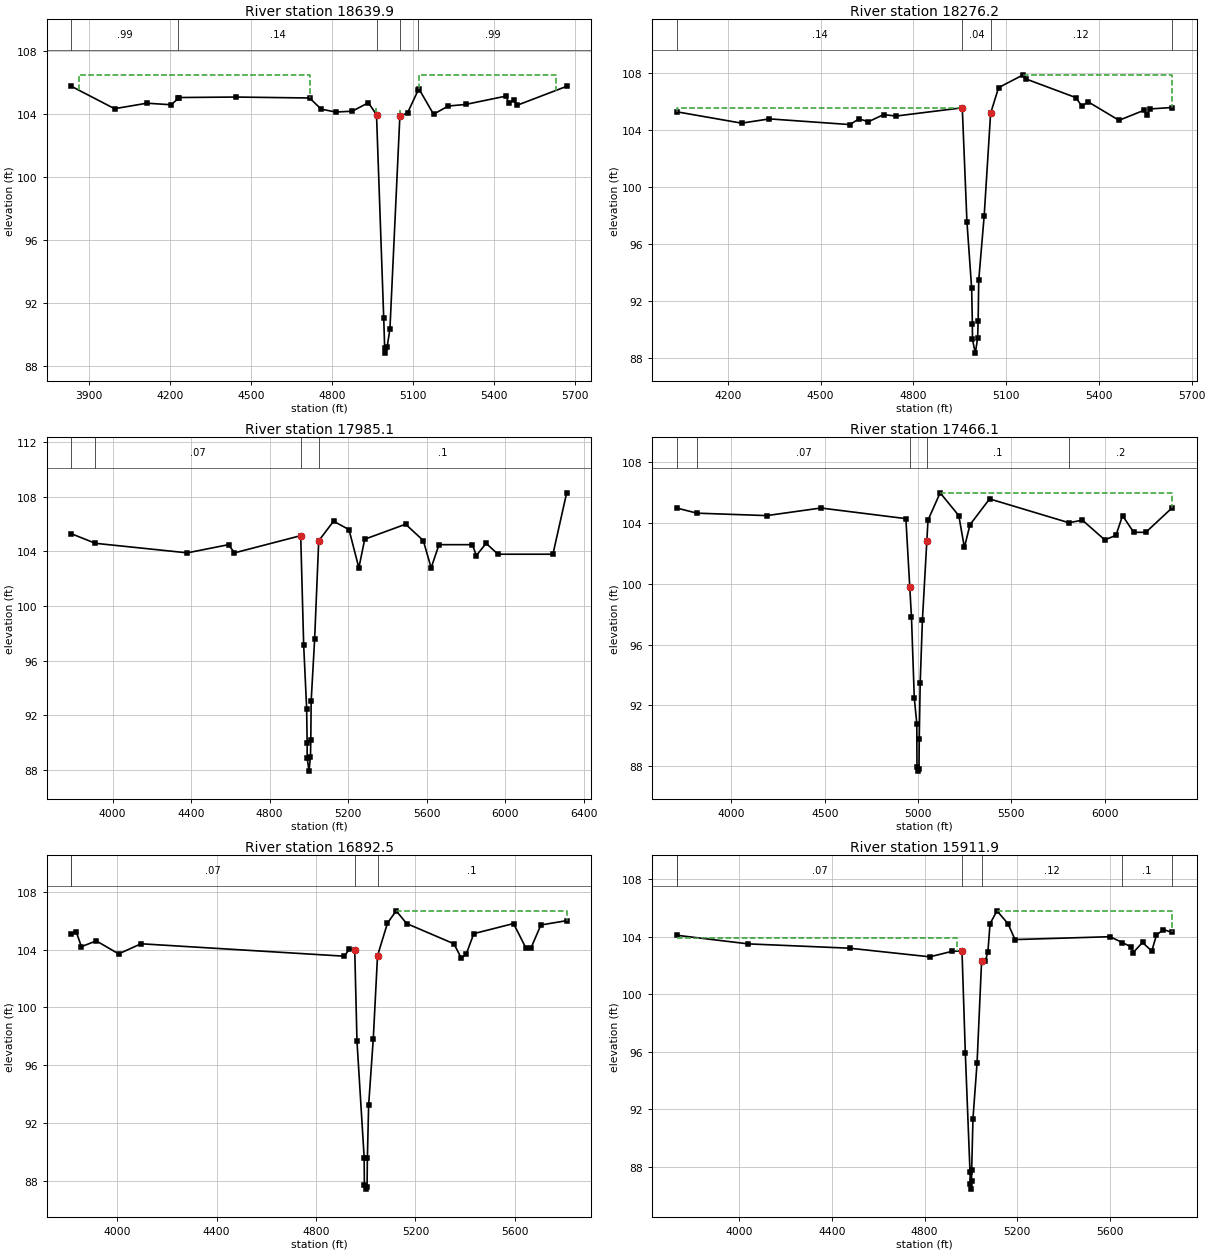
Type RM Length L Ch R = 1 ,18639.9 ,363.7,363.7,363.7
BEGIN DESCRIPTION:
Downstream Section of Bridge/Culvert/Weir
END DESCRIPTION:
XS GIS Cut Line= 6
      3087583.58     13919106.03      3087609.86     13918470.73
      3087579.96      13918254.6      3087320.66     13918256.19
      3087129.36     13918190.76      3086608.21     13918179.13
#Sta/Elev= 30
  3833.5  105.77  3993.5  104.35  4113.5   104.7  4203.5   104.6  4229.8     105
  4233.5  105.06  4443.5  105.09  4717.2  105.03  4759.8  104.32  4814.4  104.14
    4875  104.19    4935  104.73  4965.2  103.97  4991.9   91.08  4995.5   89.15
  4996.2   88.84  5004.6   89.23    5015   90.38  5051.8  103.87  5080.5  104.09
  5119.8  105.53  5122.2  105.62  5176.7     104  5231.5  104.52  5295.5  104.62
  5445.5  105.15  5455.5  104.72  5475.5   104.9  5485.5  104.56  5670.6  105.77
#Mann= 5 , 1 , 0
  3833.5     .99       0  4229.8     .14       0  4965.2     .04       0
  5051.8     .12       0  5119.8     .99       0
#XS Ineff= 4 ,-1
    3860    4717   106.5    4964    4965   104.3    5052    5053   104.2
  5122.1    5630   106.5
Permanent Ineff=
       F       F       F       F
Bank Sta=4965.2,5051.8
XS Rating Curve= 0
Exp/Cntr=.5,.3

Type RM Length L Ch R = 1 ,18276.2 ,291,291.1,290.7
BEGIN DESCRIPTION:
Cross Section 18276.2-Interpolated
END DESCRIPTION:
XS GIS Cut Line= 5
      3087589.67     13919200.42      3087613.17     13918571.46
      3087637.36     13918300.57      3087627.69     13918131.26
      3087419.68     13917642.69
#Sta/Elev= 30
  4034.1   105.3  4244.1   104.5  4334.1   104.8  4594.1   104.4  4624.1   104.8
  4654.1   104.6  4703.5   105.1  4743.5     105    4958  105.58  4973.1   97.56
  4988.3    92.9  4990.7    90.4  4990.9   89.28  5000.3   88.32  5007.7   89.39
  5009.4   90.57  5011.2   93.44  5028.9   97.99  5049.7   105.2  5075.5     107
  5155.1   107.9  5165.1   107.6  5325.1   106.3  5345.1   105.7  5365.1     106
  5465.1   104.7  5545.1   105.4  5555.1   105.1  5565.1   105.5  5636.1   105.6
#Mann= 4 , 1 , 0
  4034.1     .14       0    4958     .04       0  5049.7     .12       0
  5636.1      .2       0
#XS Ineff= 2 , 0
       0    4958  105.58  5155.1       0   107.9
Permanent Ineff=
       F       F
Bank Sta=4958,5049.7
XS Rating Curve= 0
Exp/Cntr=.3,.1

Type RM Length L Ch R = 1 ,17985.1 ,517.3,519,521.1
BEGIN DESCRIPTION:
Cross Section 17985.1
END DESCRIPTION:
XS GIS Cut Line= 4
      3087814.26      13919451.4      3087938.94     13918506.24
      3087899.97     13917819.27      3087321.84     13917155.85
#Sta/Elev= 30
  3790.7   105.3  3912.4   104.6  4380.7   103.9  4590.7   104.5  4620.7   103.9
    4958  105.16  4973.1   97.14  4988.3   92.48  4990.7   89.98  4990.9   88.86
  5000.3    87.9  5007.7   88.97  5009.4   90.15  5011.2   93.02  5028.9   97.57
  5049.7  104.78  5125.2  106.22    5204   105.6    5254   102.8    5284   104.9
  5492.1     106  5582.1   104.8  5622.1   102.8  5662.1   104.5  5832.1   104.5
  5852.1   103.7  5902.1   104.6  5962.1   103.8  6242.1   103.8  6312.1   108.3
#Mann= 4 , 1 , 0
  3790.7     .14       0  3912.4     .07       0    4958     .04       0
  5049.7      .1       0
#XS Ineff= 2 , 0
       0    4958  105.16  5125.2       0  106.22
Permanent Ineff=
       F       F
Bank Sta=4958,5049.7
XS Rating Curve= 0
Exp/Cntr=.3,.1

Type RM Length L Ch R = 1 ,17466.1 ,570,573.6,575.1
BEGIN DESCRIPTION:
Cross Section 17466.1-Interpolated
END DESCRIPTION:
XS GIS Cut Line= 6
      3088191.38     13919539.21      3088327.55     13919076.26
      3088429.67      13918606.5      3088443.28     13918293.32
      3088429.67     13917871.22      3088089.26     13916979.35
#Sta/Elev= 30
  3706.5     105  3815.6  104.66  4189.1   104.5  4479.1     105  4934.8   104.3
  4955.5   99.81  4964.8    97.8  4979.8    92.5  4993.3    90.8  4994.2   87.94
  5000.5   87.67  5005.1   87.81  5006.4    89.8  5011.4   93.46  5023.3    97.6
  5047.2  102.86  5053.3   104.2  5118.3     106  5218.3   104.5  5248.3   102.4
  5278.3   103.9  5383.3   105.6  5808.3  104.03  5880.6   104.2  6000.6   102.9
  6060.6   103.2  6095.6   104.5  6155.6   103.4  6220.6   103.4  6360.2     105
#Mann= 5 , 1 , 0
  3706.5      .2       0  3815.6     .07       0  4955.5     .04       0
  5047.2      .1       0  5808.3      .2       0
#XS Ineff= 2 , 0
       0                  5118.3       0     106
Permanent Ineff=
       F       F
Bank Sta=4955.5,5047.2
XS Rating Curve= 0
Exp/Cntr=.3,.1

Type RM Length L Ch R = 1 ,16892.5 ,980.2,980.6,981.6
BEGIN DESCRIPTION:
Cross Section 16892.5
END DESCRIPTION:
XS GIS Cut Line= 4
      3088640.52      13919402.7      3089015.67     13918637.78
      3089015.67     13918140.83      3088606.42     13917643.88
#Sta/Elev= 30
  3815.6   105.1  3835.6   105.2  3855.6   104.2  3915.6   104.6  4005.6   103.7
  4095.6   104.4    4914  103.54  4934.2  104.05  4955.5  103.96  4964.6   97.64
  4993.5    89.6  4994.2   87.69  5000.5   87.42  5005.1   87.56  5006.4   89.55
  5011.4   93.21  5030.2   97.84  5047.2  103.57  5087.3  105.83  5122.2  106.68
  5164.5   105.8  5354.5   104.4  5384.5   103.4  5404.5   103.7  5434.5   105.1
  5594.5   105.8  5644.5   104.1  5664.5   104.1  5704.5   105.7  5808.3     106
#Mann= 4 , 1 , 0
  3815.6      .2       0  3815.6     .07       0  4955.5     .04       0
  5047.2      .1       0
#XS Ineff= 2 , 0
       0  4934.2  104.05  5122.2       0  106.68
Permanent Ineff=
       F       F
Bank Sta=4955.5,5047.2
XS Rating Curve= 0
Exp/Cntr=.3,.1

Type RM Length L Ch R = 1 ,15911.9 ,498.9,498.5,496.3
BEGIN DESCRIPTION:
Cross Section 15911.9
END DESCRIPTION:
XS GIS Cut Line= 6
      3089376.21     13919409.52      3089902.39     13918879.44
      3089992.04     13918544.24      3089995.94     13918236.32
      3089941.37      13917768.6      3089793.26     13917546.44
#Sta/Elev= 30
  3728.9   104.1  4038.9   103.5  4475.8   103.2  4822.8   102.6  4917.9  102.98
  4961.7  103.01  4976.1    95.9  4996.4   87.61  4997.5   86.81  4999.7   86.44
  5002.9   87.01  5003.5   87.75  5009.1   91.34  5026.9   95.24  5046.4   102.3
  5062.1  102.29  5073.6  102.94  5082.8   104.9  5112.8   105.8  5160.7   104.9
  5190.7   103.8  5601.6     104  5654.5  103.59  5691.6   103.3  5701.6   102.9
  5741.6   103.6  5781.6     103  5801.6   104.1  5831.6   104.5  5868.6   104.3
#Mann= 6 , 1 , 0
  3728.9      .2       0  3728.9     .07       0  4961.7     .04       0
  5046.4     .12       0  5654.5      .1       0  5868.6      .2       0
#XS Ineff= 2 , 0
       0    4942   103.9  5112.8       0   105.8
Permanent Ineff=
       F       F
Bank Sta=4961.7,5046.4
XS Rating Curve= 0
Exp/Cntr=.3,.1

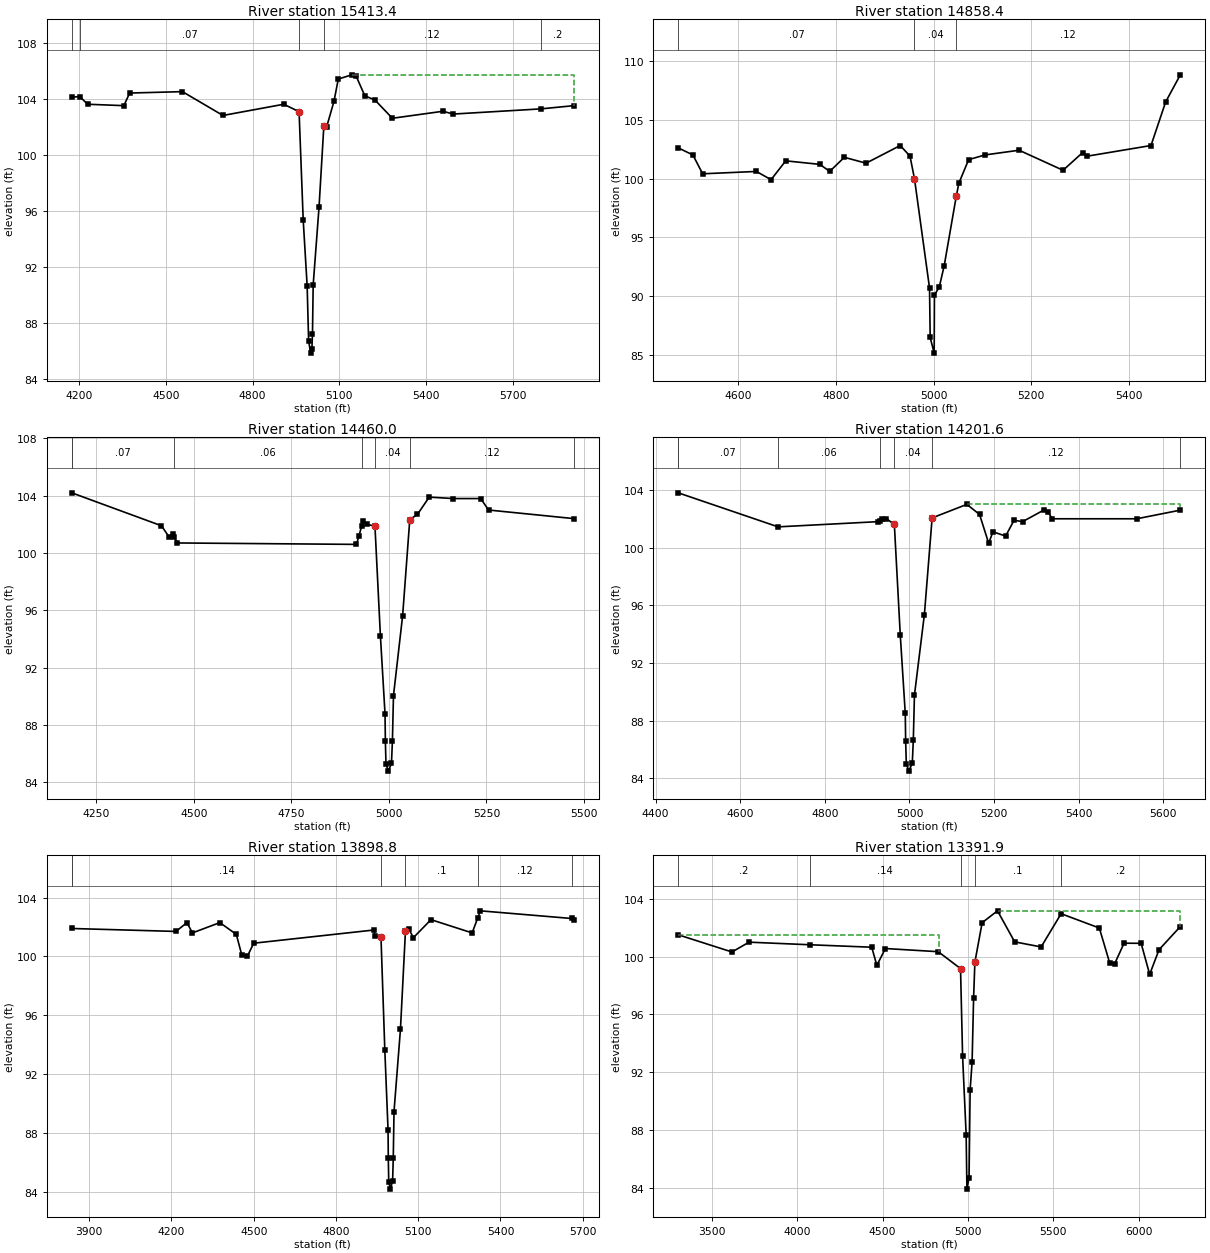
Type RM Length L Ch R = 1 ,15413.4 ,550.9,555,557.3
BEGIN DESCRIPTION:
Cross Section 15413.4-Interpolated
END DESCRIPTION:
XS GIS Cut Line= 6
      3090383.61     13919205.61      3090478.92     13918892.44
      3090492.54     13918409.06      3090485.73     13918252.47
      3090342.76     13917755.48      3090230.97     13917531.91
#Sta/Elev= 30
  4175.4   104.1    4203  104.15  4230.4   103.6  4355.4   103.5  4375.4   104.4
  4557.8   104.5  4697.8   102.8  4907.8   103.6  4960.8  103.07  4975.1   95.33
  4988.7   90.63  4993.8   86.69  5001.1   85.84    5005    86.1  5007.1   87.18
  5009.5    90.7  5029.7   96.24  5046.3  102.02  5056.3     102  5081.3   103.8
  5096.3   105.4  5143.1   105.7  5158.1   105.6  5188.1   104.2  5223.1   103.9
  5283.1   102.6  5458.1   103.1  5493.1   102.9  5796.4  103.27  5910.2   103.5
#Mann= 5 , 1 , 0
  4175.4      .2       0    4203     .07       0  4960.8     .04       0
  5046.3     .12       0  5796.4      .2       0
#XS Ineff= 2 , 0
       0                  5143.1       0   105.7
Permanent Ineff=
       F       F
Bank Sta=4960.8,5046.3
XS Rating Curve= 0
Exp/Cntr=.3,.1

Type RM Length L Ch R = 1 ,14858.4 ,364.4,398.4,431.3
BEGIN DESCRIPTION:
Cross Section 14858.4
END DESCRIPTION:
XS GIS Cut Line= 5
      3091036.61     13918949.61      3091036.61     13918949.59
       3091048.3     13918575.42      3091044.41     13918322.07
      3090794.09     13918010.14
#Sta/Elev= 30
  4477.2   102.6  4507.2     102  4527.2   100.4  4637.2   100.6  4667.2    99.9
  4697.2   101.5  4767.2   101.2  4787.2   100.6  4817.2   101.8  4861.6   101.3
  4931.6   102.8  4951.6   101.9  4960.8   99.97  4991.6    90.7  4992.9   86.51
  5001.1   85.18  5001.6    90.1  5011.6    90.8  5021.6    92.6  5046.3   98.49
  5051.6    99.6  5071.6   101.6  5104.9     102  5174.9   102.4  5264.9   100.7
  5304.9   102.2  5314.9   101.9  5444.9   102.8  5474.9   106.5  5504.9   108.8
#Mann= 3 , 1 , 0
  4477.2     .07       0  4960.8     .04       0  5046.3     .12       0
#XS Ineff= 2 , 0
       0                  5174.9       0   102.4
Permanent Ineff=
       F       F
Bank Sta=4960.8,5046.3
XS Rating Curve= 0
Exp/Cntr=.3,.1

Type RM Length L Ch R = 1 ,14460.0 ,255.5,258.4,236.6
BEGIN DESCRIPTION:
Cross Section 14460.0-Interpolated
END DESCRIPTION:
XS GIS Cut Line= 4
        3091144.     13919207.63      3091387.77     13918512.64
      3091558.92     13918341.48      3091600.42     13918035.48
#Sta/Elev= 28
  4186.8   104.2  4416.8   101.9  4436.8   101.1  4446.8   101.3  4449.8  101.12
  4456.8   100.7  4916.8   100.6  4923.3   101.2  4929.8  101.85  4933.3   102.2
  4943.3     102  4964.2  101.88  4978.2   94.21    4990   88.78  4990.9   86.87
  4992.5   85.26  4998.7   84.77  5006.6   85.33    5009    86.9  5011.7   90.04
  5035.2   95.63  5053.5  102.33  5073.3   102.7  5103.3   103.9  5165.4   103.8
  5235.4   103.8  5255.4     103  5474.2   102.4
#Mann= 7 , 1 , 0
  4186.8      .2       0  4186.8     .07       0  4449.8     .06       0
  4929.8     .07       0  4964.2     .04       0  5053.5     .12       0
  5474.2      .2       0
Bank Sta=4964.2,5053.5
XS Rating Curve= 0
Exp/Cntr=.3,.1

Type RM Length L Ch R = 1 ,14201.6 ,330.4,302.8,281
BEGIN DESCRIPTION:
Cross Section 14201.6-Interpolated
END DESCRIPTION:
XS GIS Cut Line= 5
      3091304.78     13919212.82      3091363.91     13918886.42
      3091439.63      13918756.4       3091569.3      13918564.5
      3091740.45     13918123.65
#Sta/Elev= 29
  4453.4   103.8  4689.4  101.44  4925.1   101.8  4929.4  101.88  4935.6     102
  4945.6     102  4964.2  101.61  4978.2   93.94    4990   88.51  4990.9    86.6
  4992.5   84.99  4998.7    84.5  5006.6   85.06    5009   86.63  5011.7   89.77
  5035.2   95.36  5053.5  102.06  5135.6     103  5165.6   102.3  5187.2   100.3
  5197.2   101.1  5227.2   100.8  5247.2   101.9  5267.2   101.8  5317.2   102.6
  5327.2   102.5  5337.2     102  5537.2     102  5640.1   102.6
#Mann= 7 , 1 , 0
  4453.4      .2       0  4453.4     .07       0  4689.4     .06       0
  4929.4     .07       0  4964.2     .04       0  5053.5     .12       0
  5640.1      .2       0
#XS Ineff= 2 , 0
       0                  5135.6       0     103
Permanent Ineff=
       F       F
Bank Sta=4964.2,5053.5
XS Rating Curve= 0
Exp/Cntr=.3,.1

Type RM Length L Ch R = 1 ,13898.8 ,511.8,506.9,501.3
BEGIN DESCRIPTION:
Cross Section 13898.8
END DESCRIPTION:
XS GIS Cut Line= 4
      3091753.78     13919904.52       3091718.7     13919241.92
      3091784.96     13918598.81       3091795.2     13918078.04
#Sta/Elev= 30
  3836.6   101.9  4216.6   101.7  4256.6   102.3  4276.6   101.6  4376.6   102.3
  4436.6   101.5  4456.6   100.1  4476.6     100  4500.1   100.9  4940.1   101.8
  4940.9  101.41  4964.2   101.3  4978.2   93.63    4990    88.2  4990.9   86.29
  4992.5   84.68  4998.7   84.19  5006.6   84.75    5009   86.32  5011.7   89.46
  5035.2   95.05  5053.5  101.75  5065.5  101.86  5082.6  101.28  5146.6   102.5
  5296.6   101.6  5316.5  102.59  5326.6   103.1  5659.1  102.58  5667.5   102.5
#Mann= 6 , 1 , 0
  3836.6      .2       0  3836.6     .14       0  4964.2     .04       0
  5053.5      .1       0  5316.5     .12       0  5659.1      .2       0
#XS Ineff= 2 , 0
       0  4940.1   101.8               0
Permanent Ineff=
       F       F
Bank Sta=4964.2,5053.5
XS Rating Curve= 0
Exp/Cntr=.3,.1

Type RM Length L Ch R = 1 ,13391.9 ,609.3,612.2,615.5
BEGIN DESCRIPTION:
Cross Section 13391.9-Interpolated
END DESCRIPTION:
XS GIS Cut Line= 6
      3092305.85     13920467.14      3092310.37     13919753.14
      3092276.27      13918776.7      3092269.46     13918586.07
      3092078.84     13918238.86      3091752.05     13917660.16
#Sta/Elev= 30
    3302  101.51    3617  100.32    3717     101  4073.9  100.82    4436  100.65
    4466   99.39    4516  100.56    4826  100.34  4956.4   99.17  4968.6   93.09
  4989.3   87.68  4993.9    83.9  5006.3   84.69  5012.7   90.78  5024.2   92.69
    5033   97.13  5040.6   99.62  5083.1  102.35  5173.1  103.17  5273.8  101.02
  5428.8  100.67    5546  102.97  5769.9  101.98  5829.9   99.59  5859.9   99.51
  5914.9  100.93  6014.9  100.92  6064.9   98.77  6119.9  100.48  6244.5  102.08
#Mann= 5 , 1 , 0
    3302      .2       0  4073.9     .14       0  4956.4     .04       0
  5040.6      .1       0    5546      .2       0
#XS Ineff= 2 , 0
       0    4830   101.5  5173.1       0  103.17
Permanent Ineff=
       F       F
Bank Sta=4956.4,5040.6
XS Rating Curve= 0
Exp/Cntr=.3,.1

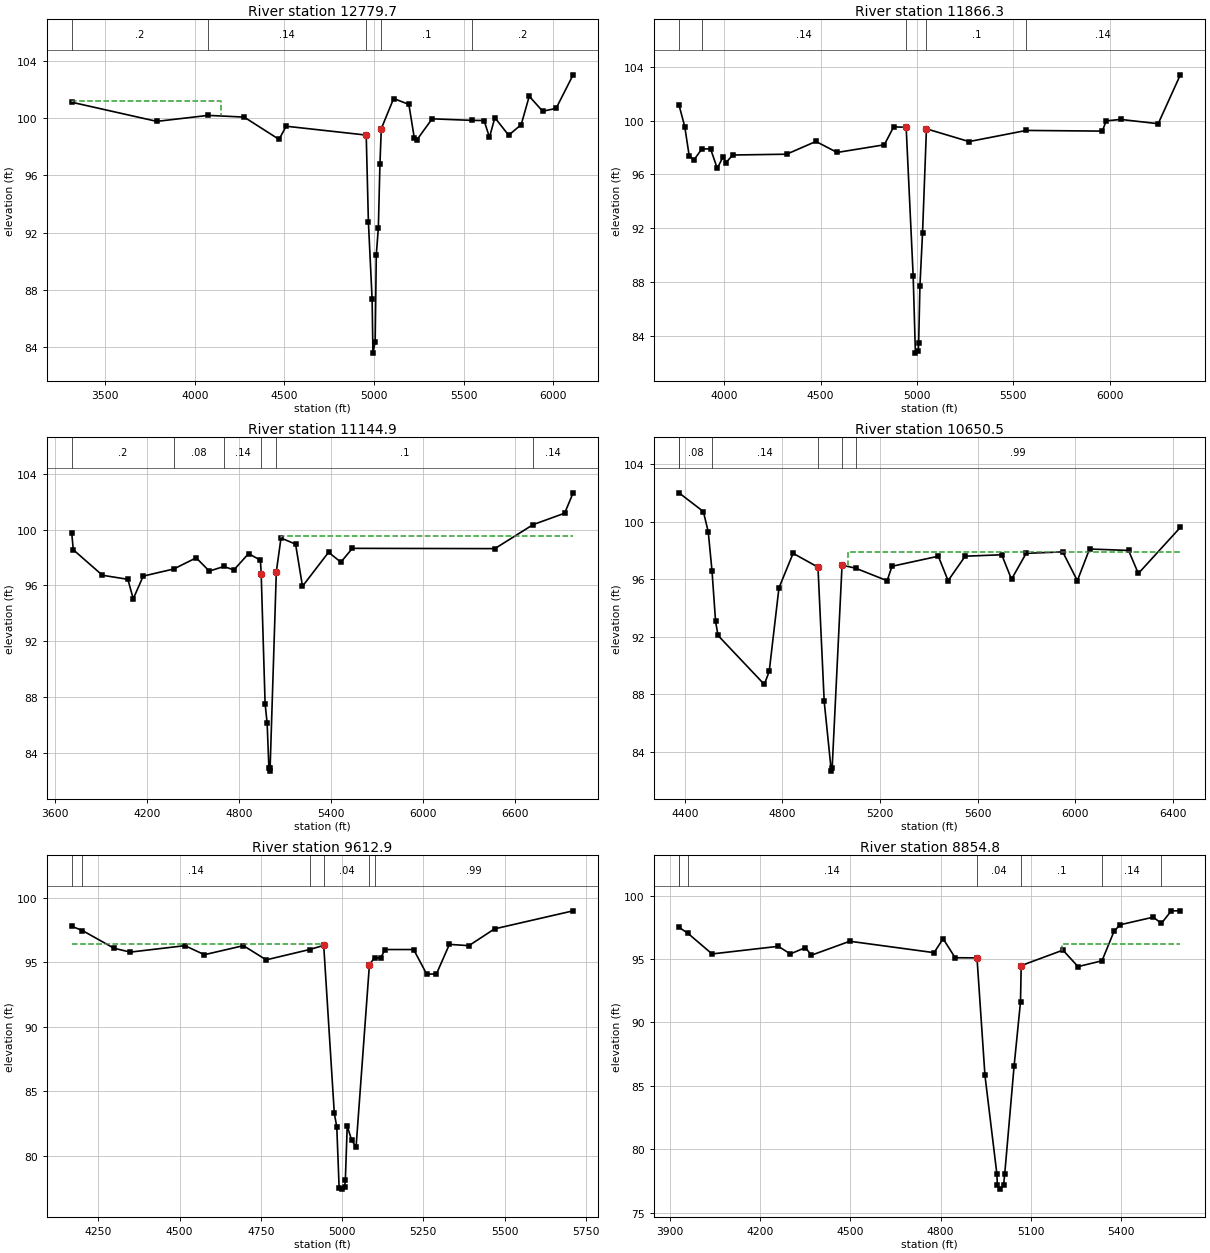
Type RM Length L Ch R = 1 ,12779.7 ,911.5,913.4,908.7
BEGIN DESCRIPTION:
Cross Section 12779.7
END DESCRIPTION:
XS GIS Cut Line= 6
      3092689.96      13920480.7      3092759.09     13919676.27
       3092884.1     13918875.54       3092891.9     13918696.25
      3092949.81     13918066.85      3093062.84     13917714.56
#Sta/Elev= 30
  3312.2  101.13  3787.2   99.79  4073.9  100.21  4274.6  100.09  4469.6   98.53
  4509.6   99.45  4956.4   98.83  4968.6   92.75  4989.3   87.34  4993.9   83.56
  5006.3   84.35  5012.7   90.44  5024.2   92.35    5033   96.79  5040.6   99.28
  5109.5  101.39  5194.5  100.98  5224.5   98.66  5239.5    98.5  5324.5   99.97
    5546   99.86  5614.5   99.85  5644.5   98.67  5674.5  100.05  5751.6   98.82
  5821.6   99.56  5866.6  101.55  5941.6   100.5  6016.6   100.7  6111.6  103.05
#Mann= 5 , 1 , 0
  3312.2      .2       0  4073.9     .14       0  4956.4     .04       0
  5040.6      .1       0    5546      .2       0
#XS Ineff= 2 , 0
       0    4148   101.2  5109.5       0  101.39
Permanent Ineff=
       F       F
Bank Sta=4956.4,5040.6
XS Rating Curve= 0
Exp/Cntr=.3,.1

Type RM Length L Ch R = 1 ,11866.3 ,726.3,721.4,710.8
BEGIN DESCRIPTION:
Cross Section 11866.3
END DESCRIPTION:
XS GIS Cut Line= 6
      3093759.52     13920052.79      3093749.87     13920000.68
      3093796.16     13918965.19      3093796.16     13918739.12
      3093753.28      13918435.1      3093122.36     13917685.11
#Sta/Elev= 30
  3764.8  101.18  3794.8   99.57  3817.8    97.4  3842.8   97.09  3883.1   97.89
  3928.7   97.92  3963.7   96.45  3993.7   97.32  4008.7   96.88  4043.7   97.45
  4323.7   97.51  4475.8   98.46  4585.8   97.64  4830.8   98.21  4879.6   99.55
  4944.3   99.51  4980.6   88.46  4992.3    82.7  5006.7   82.84  5009.1   83.42
  5015.8   87.72  5029.4   91.68  5049.6    99.4  5270.6   98.45  5568.3   99.28
  5962.7   99.23  5982.7   99.99  6057.7   100.1  6252.7   99.78  6367.7  103.42
#Mann= 5 , 1 , 0
  3764.8      .2       0  3883.1     .14       0  4944.3     .04       0
  5049.6      .1       0  5568.3     .14       0
Bank Sta=4944.3,5049.6
XS Rating Curve= 0
Exp/Cntr=.3,.1

Type RM Length L Ch R = 1 ,11144.9 ,534.5,494.4,482
BEGIN DESCRIPTION:
Cross Section 11144.9-Interpolated
END DESCRIPTION:
XS GIS Cut Line= 6
       3094390.8     13920066.22       3094475.3      13919777.5
      3094566.68     13918931.14       3094386.8     13918225.24
      3094019.16     13917864.41       3093210.8     13917556.47
#Sta/Elev= 30
  3711.3   99.75  3721.3   98.55  3911.3   96.72  4077.1   96.43  4112.1   95.03
  4177.1   96.66  4375.8   97.17  4522.4   97.97  4607.4   97.02  4703.2   97.35
  4767.4    97.1  4863.6   98.27  4940.9    97.8  4945.8   96.84  4971.3   87.52
  4984.6   86.11  4996.1   82.89  5000.4   82.68  5003.9   82.88  5044.5   96.98
  5074.9   99.39  5169.9   98.95  5214.9   95.93  5384.9   98.37  5464.9   97.66
  5539.9   98.65  6468.4   98.63  6717.6  100.35  6923.4  101.17  6978.4  102.63
#Mann= 6 , 1 , 0
  3711.3      .2       0  4375.8     .08       0  4703.2     .14       0
  4945.8     .04       0  5044.5      .1       0  6717.6     .14       0
#XS Ineff= 2 , 0
       0  4863.6   98.27    5075       0    99.5
Permanent Ineff=
       F       F
Bank Sta=4945.8,5044.5
XS Rating Curve= 0
Exp/Cntr=.3,.1

Type RM Length L Ch R = 1 ,10650.5 ,1026.3,1037.6,1046.7
BEGIN DESCRIPTION:
Cross Section 10650.5
END DESCRIPTION:
XS GIS Cut Line= 4
      3095064.73     13919286.62      3095053.18      13918818.8
      3094926.12     13918530.03      3094439.84     13917354.27
#Sta/Elev= 30
  4375.8     102  4475.8   100.7  4495.8    99.3  4511.2    96.6  4525.8    93.1
  4535.8    92.1  4725.8    88.7  4745.8    89.6  4785.8    95.4  4843.8    97.8
  4945.8   96.84  4971.3   87.52  5000.4   82.68  5003.9   82.88  5044.5   96.98
  5099.8   96.77  5229.3    95.9  5249.3    96.9  5439.3    97.6  5479.3    95.9
  5549.3    97.6  5699.3    97.7  5739.3      96  5799.3    97.8  5949.3    97.9
  6009.3    95.9  6059.3    98.1  6219.3      98  6259.3    96.4  6431.6    99.6
#Mann= 6 , 1 , 0
  4375.8      .2       0  4375.8     .08       0  4511.2     .14       0
  4945.8     .04       0  5044.5      .1       0  5099.8     .99       0
#XS Ineff= 2 , 0
       0  4843.8    97.8    5069       0    97.9
Permanent Ineff=
       F       F
Bank Sta=4945.8,5044.5
XS Rating Curve= 0
Exp/Cntr=.3,.1

Type RM Length L Ch R = 1 ,9612.9  ,734.4,758.1,782.2
BEGIN DESCRIPTION:
Cross Section 9612.9
END DESCRIPTION:
XS GIS Cut Line= 6
      3096150.35     13919208.02      3096150.35     13918859.95
      3096017.82     13918559.83      3095920.38     13918197.35
      3095787.86     13917986.87      3095702.11     13917760.81
#Sta/Elev= 30
  4168.5    97.8  4201.6   97.47  4298.5    96.1  4348.5    95.8  4516.6    96.3
  4576.6    95.6  4696.6    96.3  4766.6    95.2    4900      96  4943.5   96.32
  4976.1    83.3  4983.7   82.25    4991   77.48  4999.2   77.43  5007.7   77.57
    5010    78.1  5015.8   82.32  5029.1   81.25    5043   80.69  5084.1   94.83
    5100   95.37  5118.6   95.33  5131.9      96  5220.1      96  5260.1    94.1
  5290.1    94.1  5330.1    96.4  5390.1    96.3  5468.8    97.6  5710.6      99
#Mann= 6 , 1 , 0
  4168.5      .1       0  4201.6     .14       0    4900     .07       0
  4943.5     .04       0  5084.1     .07       0    5100     .99       0
#XS Ineff= 2 , 0
       0  4936.9   96.41  5220.1       0      96
Permanent Ineff=
       F       F
Bank Sta=4943.5,5084.1
XS Rating Curve= 0
Exp/Cntr=.3,.1

Type RM Length L Ch R = 1 ,8854.8  ,128.1,233.5,237.4
BEGIN DESCRIPTION:
Cross Section 8854.8-Interpolated
END DESCRIPTION:
XS GIS Cut Line= 5
      3096159.77     13919224.98      3096451.01     13918737.98
      3096718.39     13918437.18      3096737.49     13918222.32
      3096757.16     13917742.72
#Sta/Elev= 30
  3930.8    97.5  3959.8   97.04  4040.8    95.4  4260.8      96  4300.8    95.4
  4350.8    95.9  4370.8    95.3  4498.3    96.4  4778.3    95.5  4808.3    96.6
  4848.3    95.1  4920.9   95.09  4947.3   85.82  4986.9   78.05  4988.5   77.16
  4997.8   76.85  5009.3    77.2    5013   78.05    5044   86.53  5065.4   91.62
  5067.7   94.48  5206.4    95.7  5256.4    94.4  5336.1   94.86  5376.4    97.2
  5396.4    97.7  5506.4    98.3  5533.4   97.81  5566.4    98.8  5596.4    98.8
#Mann= 7 , 1 , 0
  3930.8      .2       0  3930.8      .1       0  3959.8     .14       0
  4920.9     .04       0  5067.7      .1       0  5336.1     .14       0
  5533.4      .1       0
#XS Ineff= 2 , 0
       0    4806    96.2    5202       0    96.2
Permanent Ineff=
       F       F
Bank Sta=4920.9,5067.7
XS Rating Curve= 0
Exp/Cntr=.5,.3