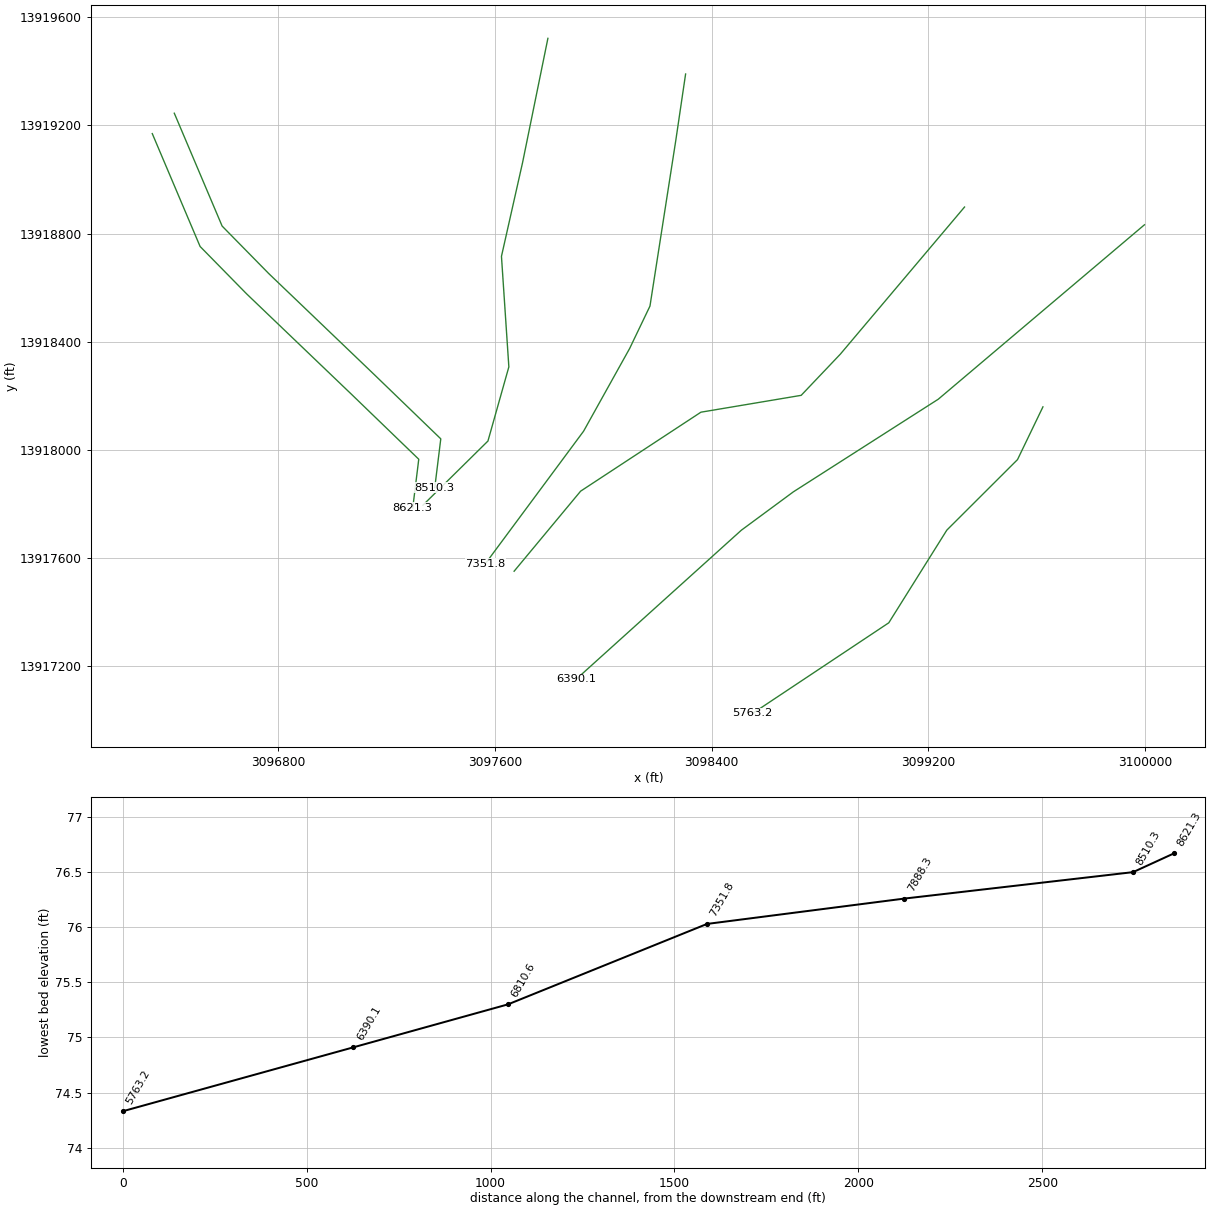
HEC-RAS study P145-00-00.PRJ: P145-00-00

--- P145-00-00.g01 (geometry) --- (continued)

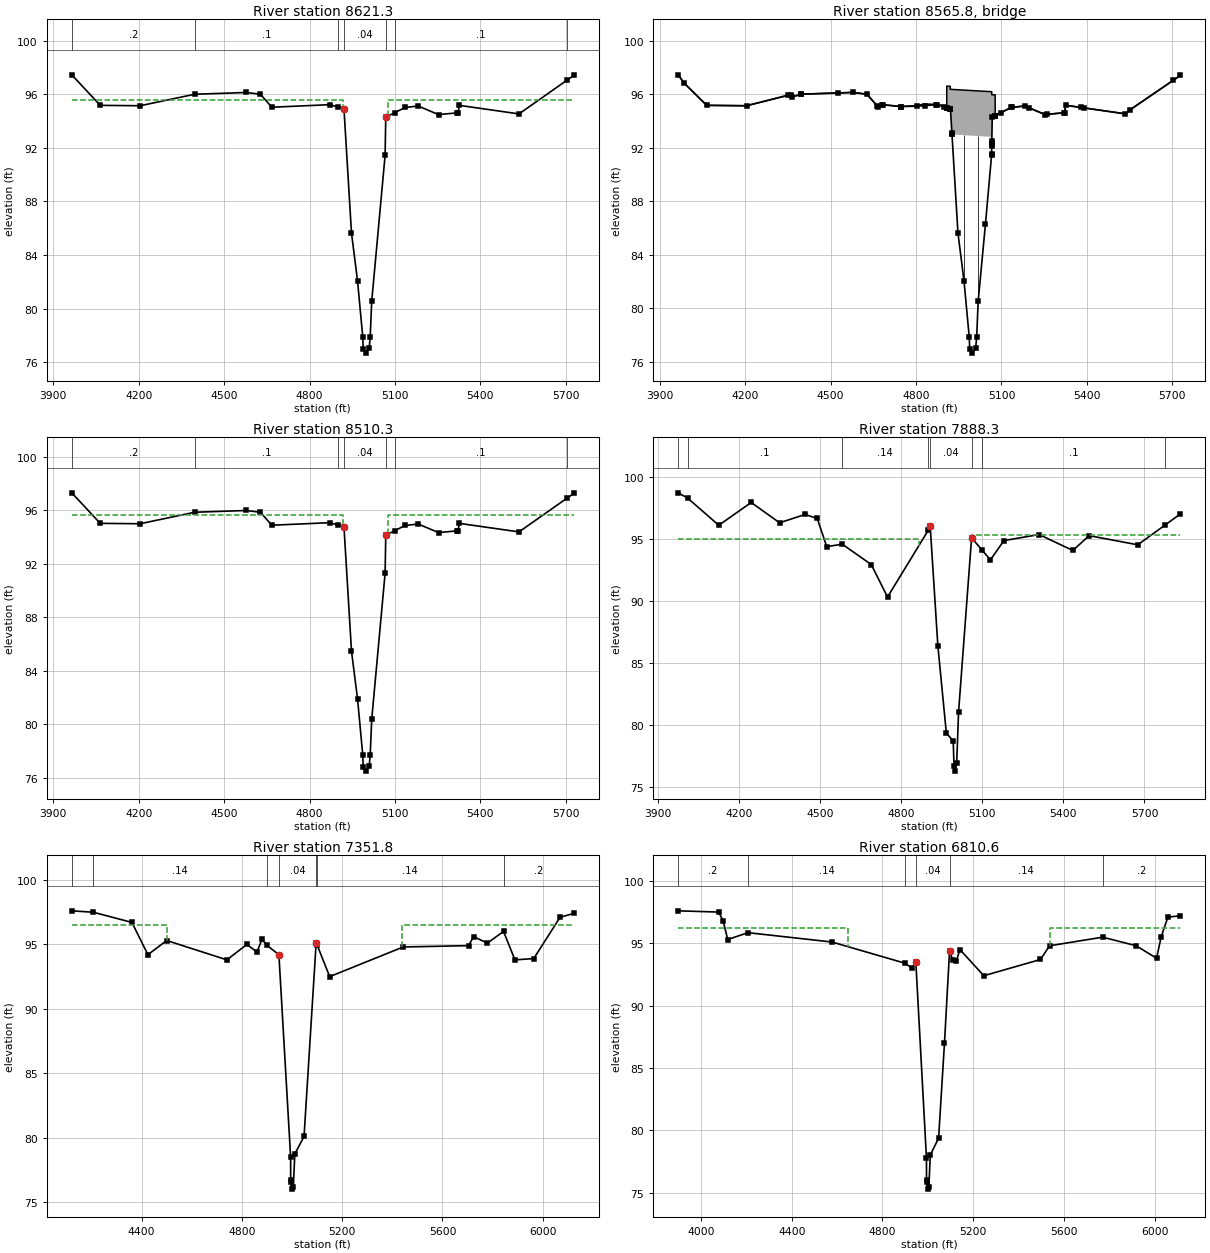
Type RM Length L Ch R = 1 ,8621.3  ,111,111,111
BEGIN DESCRIPTION:
Upstream Section of Bridge/Culvert/Weir
END DESCRIPTION:
XS GIS Cut Line= 6
      3096334.01     13919169.92      3096510.64      13918752.2
      3096682.62     13918576.64      3097068.49     13918206.36
      3097318.21      13917964.7        3097296.     13917784.35
#Sta/Elev= 30
  3964.9   97.46  4064.9   95.18  4204.9   95.15  4396.8   96.01  4577.4   96.14
  4627.4   96.01  4667.4   95.04  4871.3   95.23    4900   95.05  4920.9   94.91
  4947.3   85.64  4968.6   82.05  4986.9   77.87  4988.5   76.98  4997.8   76.67
  5009.3   77.02    5013   77.87  5018.3   80.54  5065.3   91.44  5067.7    94.3
    5100   94.64  5135.3   95.02  5181.7   95.13  5252.9   94.49    5319   94.62
    5322   94.63  5325.6   95.18  5535.6   94.54  5703.4   97.05  5728.2   97.41
#Mann= 7 , 1 , 0
  3964.9      .2       0  4396.8      .1       0    4900     .07       0
  4920.9     .04       0  5067.7     .07       0    5100      .1       0
  5703.4      .2       0
#XS Ineff= 2 , 0
       0  4915.9    95.6  5076.2       0    95.6
Permanent Ineff=
       F       F
Bank Sta=4920.9,5067.7
XS Rating Curve= 0
Exp/Cntr=.5,.3

Type RM Length L Ch R = 3 ,8565.8  ,,,
BEGIN DESCRIPTION:
ELLA BOULEVARD
Structure ID: P45-6
END DESCRIPTION:
Bridge Culvert--1,0,-1,-1, 0
Deck Dist Width WeirC Skew NumUp NumDn MinLoCord MaxHiCord MaxSubmerge Is_Ogee
10,91,2.6,0, 37, 37, , , .95, 0, 1,1,,
  3964.9  3984.9  4064.9  4204.9  4359.9  4364.9  4396.8  4577.4  4627.4  4667.4
  4681.8  4748.4  4803.1    4830  4874.1 4907.89    4908  4920.1  4920.3  4920.9
  4926.3  5065.9 5065.99  5066.1  5066.2  5067.7    5078 5078.11  5135.3  5181.7
  5252.9    5319    5322  5325.6  5535.6  5552.3  5728.2
   97.45   96.85   95.17   95.14   95.96    95.8   96.01   96.14   96.01   95.04
   95.22   95.09   95.15   95.28   95.23   95.11   96.61   96.59   96.37   96.37
   96.36   96.19   96.12   96.04   95.96   95.96   95.96   94.46   95.02   95.13
   94.49   94.62   94.63   95.18   94.54   94.85    97.4
   97.45   96.85   95.17   95.14   95.96    95.8      96   96.13      96   95.03
   95.21   95.08   95.11   95.15   95.22   94.99   94.99   94.91    94.9    94.9
      93   92.81   92.74   92.38    92.5   94.29    94.4    94.4   95.01   95.12
   94.48   94.61   94.62   95.17   94.53   94.84    97.4
  3964.9  3984.9  4064.9  4204.9  4359.9  4364.9  4396.8  4577.4  4627.4  4667.4
  4681.8  4748.4  4803.1    4830  4874.1 4907.89    4908  4920.1  4920.3  4920.9
  4926.3  5065.9 5065.99  5066.1  5066.2  5067.7    5078 5078.11  5135.3  5181.7
  5252.9    5319    5322  5325.6  5535.6  5552.3  5728.2
   97.45   96.85   95.17   95.14   95.96    95.8   96.01   96.14   96.01   95.04
   95.22   95.09   95.15   95.28   95.23   95.11   96.61   96.59   96.37   96.37
   96.36   96.19   96.12   96.04   95.96   95.96   95.96   94.46   95.02   95.13
   94.49   94.62   94.63   95.18   94.54   94.85    97.4
   97.29   96.69   95.01   94.98    95.8   95.64   95.84   95.97   95.84   94.87
   95.05   94.92   94.95   94.99   95.06   94.83   94.83   94.75   94.74   94.74
   92.84   92.65   92.58   92.22   92.34   94.13   94.24   94.24   94.85   94.96
   94.32   94.45   94.46   95.01   94.37   94.68   97.24
Pier Skew, UpSta & Num, DnSta & Num=  ,4968.6, 2 ,4968.6, 2 , 0 , 0 , 0 ,,
     1.4     1.4
   80.88   93.93
     1.4     1.4
   80.72   93.77
Pier Skew, UpSta & Num, DnSta & Num=  ,5018.3, 2 ,5018.3, 2 , 0 , 0 , 0 ,,
     1.4     1.4
   79.18   93.87
     1.4     1.4
   79.02   93.71
BR Coef= 1 , 1 , 0 ,1.25, 0 ,,,.8,0,2,0,
WSPro=,,,, 1 ,,,, 0 ,,,, 0 ,,,,-1 ,-1 ,-1 , 0 , 0 , 0 , 0 , 0
BR U #Sta/Elev= 67
  3964.9   97.45  3984.9   96.85  4064.9   95.17  4204.9   95.14  4349.9   95.93
  4359.9   95.96  4364.9    95.8  4396.8      96  4397.4      96  4526.8   96.09
  4577.4   96.13  4627.4      96  4664.2   95.11  4667.4   95.03  4681.8   95.21
  4683.5   95.21  4746.3   95.08  4748.4   95.08  4803.1   95.11    4830   95.15
  4871.3   95.22  4874.1   95.22    4900   95.04 4907.89   94.99    4908   94.99
 4908.11   94.99  4920.1   94.91  4920.3    94.9  4920.9    94.9 4926.11   93.07
 4926.23   93.03  4926.3      93  4947.3   85.63  4968.6   82.04  4986.9   77.86
  4988.5   76.97  4997.8   76.66  5009.3   77.01    5013   77.86  5018.3   80.53
    5044   86.34  5065.3   91.43  5065.4   91.55  5065.9   92.15 5065.99   92.25
  5066.1   92.38  5066.2    92.5  5067.7   94.29 5077.89    94.4    5078    94.4
 5078.11    94.4    5100   94.63  5135.3   95.01  5137.4   95.01  5181.7   95.12
  5195.9   94.99  5252.9   94.48    5259   94.49    5319   94.61    5322   94.62
  5325.6   95.17  5378.9   95.01  5388.9   94.98  5535.6   94.53  5552.3   94.84
  5703.4   97.04  5728.2    97.4
BR U #Mann= 7
  3964.9      .2  4396.8      .1    4900     .07  4920.9     .04  5067.7     .07
    5100      .1  5703.4      .2
BR U Banks=4920.9,5067.7
BR D #Sta/Elev= 67
  3964.9   97.29  3984.9   96.69  4064.9   95.01  4204.9   94.98  4349.9   95.77
  4359.9    95.8  4364.9   95.64  4396.8   95.84  4397.4   95.84  4526.8   95.93
  4577.4   95.97  4627.4   95.84  4664.2   94.95  4667.4   94.87  4681.8   95.05
  4683.5   95.05  4746.3   94.92  4748.4   94.92  4803.1   94.95    4830   94.99
  4871.3   95.06  4874.1   95.06    4900   94.88 4907.89   94.83    4908   94.83
 4908.11   94.83  4920.1   94.75  4920.3   94.74  4920.9   94.74 4926.11   92.91
 4926.23   92.87  4926.3   92.84  4947.3   85.47  4968.6   81.88  4986.9    77.7
  4988.5   76.81  4997.8    76.5  5009.3   76.85    5013    77.7  5018.3   80.37
    5044   86.18  5065.3   91.27  5065.4   91.39  5065.9   91.99 5065.99   92.09
  5066.1   92.22  5066.2   92.34  5067.7   94.13 5077.89   94.24    5078   94.24
 5078.11   94.24    5100   94.47  5135.3   94.85  5137.4   94.85  5181.7   94.96
  5195.9   94.83  5252.9   94.32    5259   94.33    5319   94.45    5322   94.46
  5325.6   95.01  5378.9   94.85  5388.9   94.82  5535.6   94.37  5552.3   94.68
  5703.4   96.88  5728.2   97.24
BR D #Mann= 7
  3964.9      .2  4396.8      .1    4900     .07  4920.9     .04  5067.7     .07
    5100      .1  5703.4      .2
BR D Banks=4920.9,5067.7
BC Design=,, 0 ,, 0 ,,,,,,

Type RM Length L Ch R = 1 ,8510.3  ,622,622,622
BEGIN DESCRIPTION:
Downstream Section of Bridge/Culvert/Weir
END DESCRIPTION:
XS GIS Cut Line= 6
      3096415.36     13919245.43        3096592.     13918827.72
      3096763.98     13918652.16      3097149.85     13918281.88
      3097399.57     13918040.22      3097377.35     13917859.86
#Sta/Elev= 30
  3964.9   97.29  4064.9   95.01  4204.9   94.98  4396.8   95.84  4577.4   95.97
  4627.4   95.84  4667.4   94.87  4871.3   95.06    4900   94.88  4920.9   94.74
  4947.3   85.47  4968.6   81.88  4986.9    77.7  4988.5   76.81  4997.8    76.5
  5009.3   76.85    5013    77.7  5018.3   80.37  5065.3   91.27  5067.7   94.13
    5100   94.47  5135.3   94.85  5181.7   94.96  5252.9   94.32    5319   94.45
    5322   94.46  5325.6   95.01  5535.6   94.37  5703.4   96.88  5728.2   97.24
#Mann= 7 , 1 , 0
  3964.9      .2       0  4396.8      .1       0    4900     .07       0
  4920.9     .04       0  5067.7     .07       0    5100      .1       0
  5703.4      .2       0
#XS Ineff= 2 , 0
       0  4915.9    95.6  5076.2       0    95.6
Permanent Ineff=
       F       F
Bank Sta=4920.9,5067.7
XS Rating Curve= 0
Exp/Cntr=.5,.3

Type RM Length L Ch R = 1 ,7888.3  ,563.1,536.5,502
BEGIN DESCRIPTION:
Cross Section 7888.3
END DESCRIPTION:
XS GIS Cut Line= 6
      3097795.16     13919522.55      3097701.62     13919062.63
      3097623.66     13918715.74      3097650.95     13918306.48
      3097573.74     13918032.11      3097333.82     13917794.92
#Sta/Elev= 30
  3975.2   98.75  4010.2   98.32  4125.2   96.13  4245.2   97.97  4350.2   96.33
  4444.5      97  4489.5   96.68  4524.5    94.4    4582    94.6  4689.5   92.95
  4749.5   90.33    4900   95.72  4907.4   96.04  4935.7   86.39  4967.1   79.33
  4992.5    78.7  4995.6   76.64    5000   76.26  5005.4   76.94  5012.4   81.06
  5060.5   95.12    5100    94.1  5130.1   93.33  5180.1   94.89  5310.2   95.38
  5435.2   94.09  5495.3   95.29  5675.3   94.55  5776.5   96.15  5832.7   97.04
#Mann= 8 , 1 , 0
  3975.2      .2       0  4010.2      .1       0    4582     .14       0
    4900     .07       0  4907.4     .04       0  5060.5     .07       0
    5100      .1       0  5776.5      .2       0
#XS Ineff= 2 , 0
       0  4864.8   95.03    5063       0   95.38
Permanent Ineff=
       F       F
Bank Sta=4907.4,5060.5
XS Rating Curve= 0
Exp/Cntr=.3,.1

Type RM Length L Ch R = 1 ,7351.8  ,624.8,541.2,464.7
BEGIN DESCRIPTION:
Cross Section 7351.8-Interpolated
END DESCRIPTION:
XS GIS Cut Line= 6
      3098303.71     13919390.47      3098267.44     13919144.34
      3098172.13     13918531.61      3098097.24     13918375.02
      3097927.04     13918068.65      3097564.29     13917578.27
#Sta/Elev= 30
  4121.2    97.6  4207.2   97.49  4361.2    96.7    4425    94.2    4500    95.3
    4740    93.8    4820      95    4860    94.4    4880    95.4    4900   94.92
  4947.5    94.2  4994.3   78.51  4994.5   76.74  4994.7   76.61  4999.8   76.03
    5005   76.18    5011   78.76  5047.8   80.11  5096.2   95.14    5100   94.95
  5150.1    92.5  5443.6    94.8  5704.1    94.9  5724.1    95.6  5779.1    95.1
  5843.6      96  5889.1    93.8  5964.1    93.9  6069.1    97.1  6124.1    97.4
#Mann= 7 , 1 , 0
  4121.2      .2       0  4207.2     .14       0    4900     .07       0
  4947.5     .04       0  5096.2     .07       0    5100     .14       0
  5843.6      .2       0
#XS Ineff= 2 , 0
       0    4500    96.5    5440       0    96.5
Permanent Ineff=
       F       F
Bank Sta=4947.5,5096.2
XS Rating Curve= 0
Exp/Cntr=.3,.1

Type RM Length L Ch R = 1 ,6810.6  ,379.9,420.5,446.1
BEGIN DESCRIPTION:
Cross Section 6810.6
END DESCRIPTION:
XS GIS Cut Line= 6
      3099333.89     13918898.19      3098874.81     13918353.25
       3098730.6     13918201.24      3098360.32     13918138.88
      3097915.99     13917846.56      3097670.43     13917550.33
#Sta/Elev= 30
  3899.6    97.6  4077.7    97.5  4097.7    96.8  4117.7    95.3  4207.2   95.85
  4577.7    95.1    4900    93.4  4929.5   93.02  4947.5   93.47  4994.3   77.78
  4994.5   76.01  4994.7   75.88  4999.8    75.3    5005   75.45    5011   78.03
  5047.8   79.38  5073.8   87.02  5096.2   94.41  5109.6   93.66  5125.9   93.58
  5141.7    94.5  5247.2    92.4  5497.2    93.7  5537.2    94.8  5771.6   95.49
  5919.1    94.8  6009.1    93.8  6029.1    95.5  6059.1    97.1  6113.8    97.2
#Mann= 6 , 1 , 0
  3899.6      .2       0  4207.2     .14       0    4900     .07       0
  4947.5     .04       0  5096.2     .14       0  5771.6      .2       0
#XS Ineff= 2 , 0
       0    4650    96.2    5540       0    96.2
Permanent Ineff=
       F       F
Bank Sta=4947.5,5096.2
XS Rating Curve= 0
Exp/Cntr=.3,.1

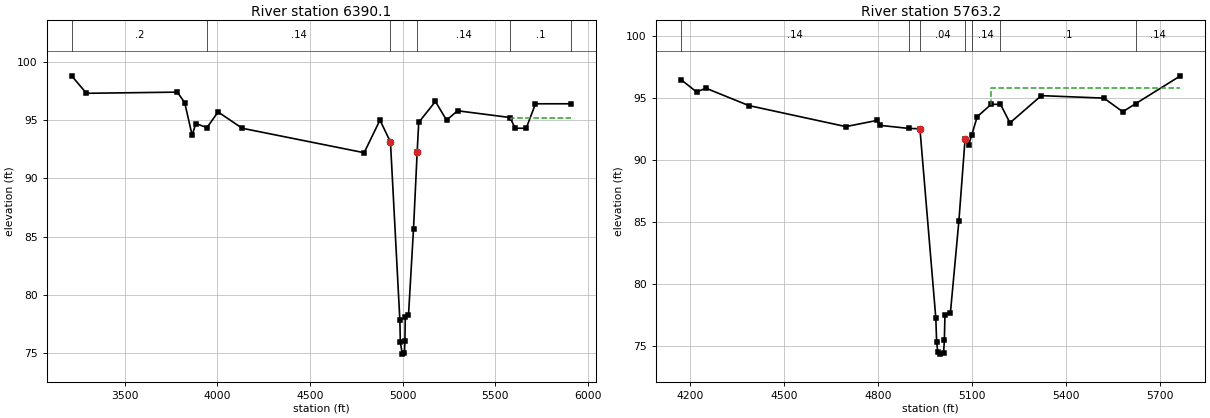
Type RM Length L Ch R = 1 ,6390.1  ,580.8,626.9,633.1
BEGIN DESCRIPTION:
Cross Section 6390.1-Interpolated
END DESCRIPTION:
XS GIS Cut Line= 5
      3099998.32     13918832.47      3099236.88     13918186.91
      3098701.89     13917844.18      3098509.63     13917702.08
      3097899.42     13917150.38
#Sta/Elev= 30
  3214.1    98.8  3294.1    97.3  3784.1    97.4  3824.1    96.5  3864.1    93.7
  3884.1    94.7  3944.6   94.36  4004.1    95.7  4134.1    94.3  4792.3    92.2
  4877.7      95  4934.3   93.11  4985.1    77.8  4987.6   75.91  4998.3   74.91
  5009.8   74.98  5012.3   76.03  5014.2   78.06  5031.6   78.24  5058.7   85.67
  5078.5   92.29  5086.8    94.8  5176.8    96.6  5236.8      95  5296.8    95.8
    5580   95.22  5606.8    94.3  5666.8    94.3  5716.8    96.4  5909.4    96.4
#Mann= 6 , 1 , 0
  3214.1      .2       0  3944.6     .14       0  4934.3     .04       0
  5078.5     .14       0    5580      .1       0  5909.4      .2       0
#XS Ineff= 2 , 0
       0  4004.1    95.7  5586.8       0    95.2
Permanent Ineff=
       F       F
Bank Sta=4934.3,5078.5
XS Rating Curve= 0
Exp/Cntr=.3,.1

Type RM Length L Ch R = 1 ,5763.2  ,520.6,520.2,501
BEGIN DESCRIPTION:
Cross Section 5763.2
END DESCRIPTION:
XS GIS Cut Line= 6
      3099623.46     13918158.62      3099529.62     13917963.49
      3099268.48     13917702.34       3099054.1     13917359.35
      3098551.31     13917024.15      3098551.31     13917024.15
#Sta/Elev= 30
  4171.3    96.5  4221.3    95.5  4251.3    95.8  4387.9    94.4  4697.9    92.7
  4797.2    93.2  4807.2    92.8    4900   92.55  4934.3   92.53  4985.1   77.22
  4987.6   75.33  4991.3   74.49  4998.3   74.33  5009.8    74.4  5012.3   75.45
  5014.2   77.48  5031.6   77.66  5058.7   85.09  5078.5   91.71    5090   91.23
    5100   92.05  5117.2    93.5  5161.7    94.5  5191.5    94.5  5221.7      93
  5321.7    95.2  5521.7      95  5581.7    93.9  5622.8   94.55  5765.9    96.8
#Mann= 7 , 1 , 0
  4171.3     .14       0    4900     .07       0  4934.3     .04       0
  5078.5     .07       0    5100     .14       0  5191.5      .1       0
  5622.8     .14       0
#XS Ineff= 2 , 0
       0                    5161       0    95.8
Permanent Ineff=
       F       F
Bank Sta=4934.3,5078.5
XS Rating Curve= 0
Exp/Cntr=.3,.1