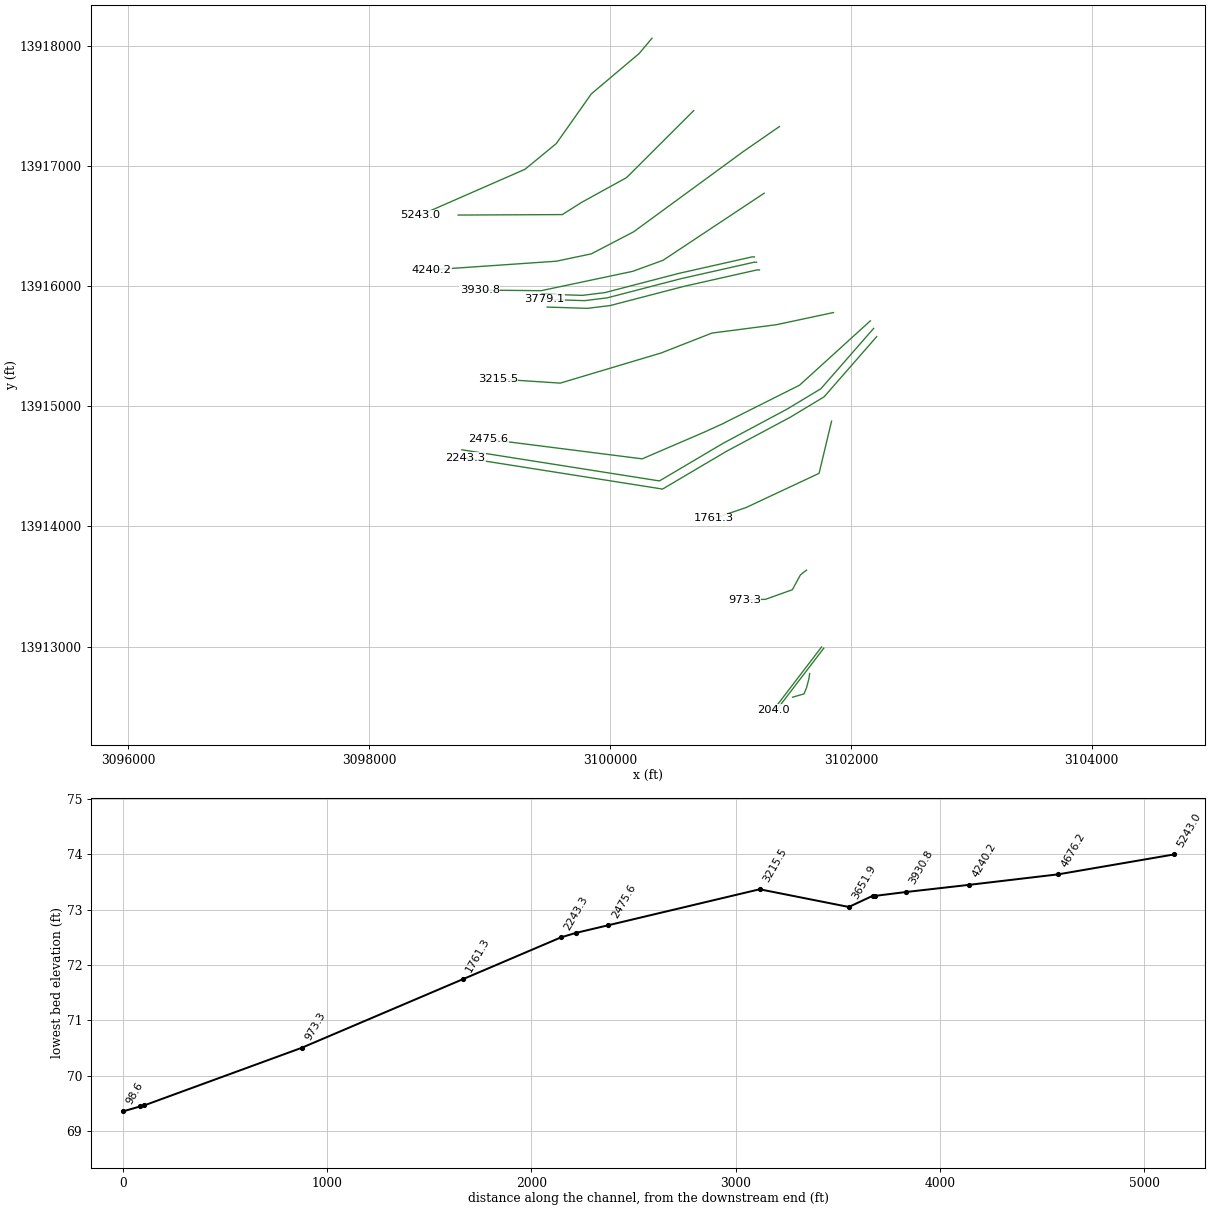
HEC-RAS study P145-00-00.PRJ: P145-00-00

--- P145-00-00.g01 (geometry) --- (continued)

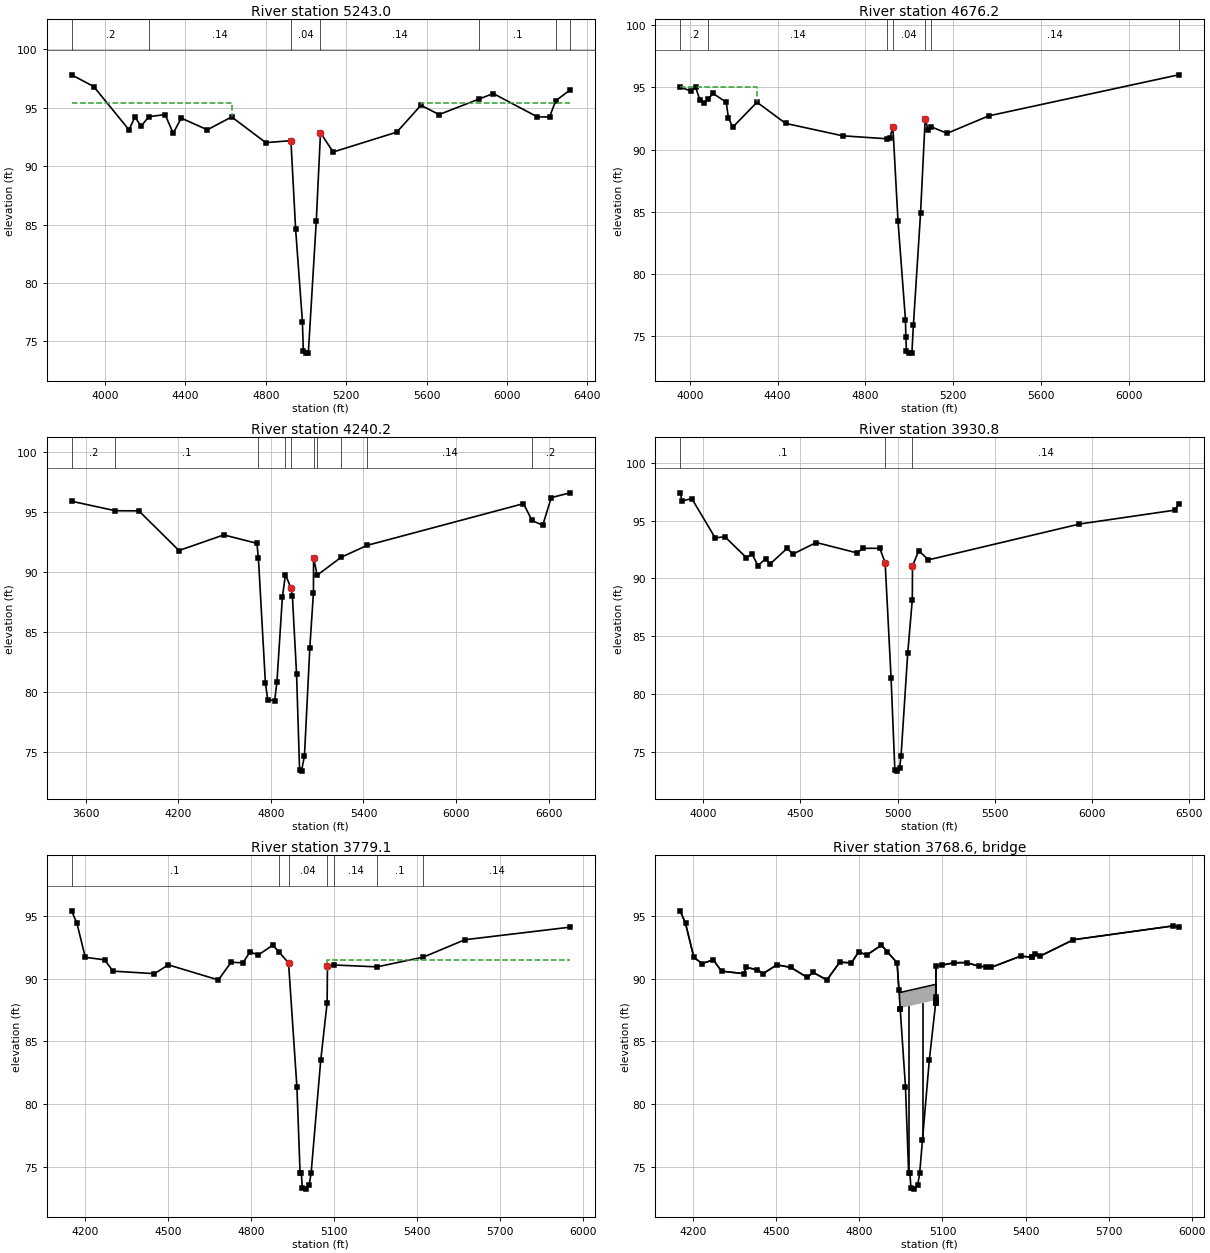
Type RM Length L Ch R = 1 ,5243.0  ,591.3,566.8,555.6
BEGIN DESCRIPTION:
Cross Section 5243.0-Interpolated
END DESCRIPTION:
XS GIS Cut Line= 6
      3100348.69     13918063.03      3100242.17     13917936.13
      3099844.41     13917599.57      3099553.74     13917186.52
      3099293.67     13916972.34      3098421.67     13916589.88
#Sta/Elev= 30
  3833.5    97.8  3943.5    96.8  4119.1    93.1  4149.1    94.2  4179.1    93.4
  4217.7   94.22  4299.1    94.4  4339.1    92.8  4379.1    94.1  4509.1    93.1
  4630.2    94.2  4800.2      92  4925.1   92.17  4948.5   84.59  4982.3    76.7
  4986.9   74.14  4998.2      74  5011.8   74.03  5051.2   85.27  5072.3   92.84
  5135.3    91.2  5452.2    92.9  5572.2    95.2  5662.2    94.4    5863   95.74
  5932.2    96.2  6152.2    94.2  6212.2    94.2  6243.1   95.59  6314.4    96.5
#Mann= 7 , 1 , 0
  3833.5      .2       0  4217.7     .14       0  4925.1     .04       0
  5072.3     .14       0    5863      .1       0  6243.1     .14       0
  6314.4      .2       0
#XS Ineff= 2 , 0
       0  4630.2    95.4    5572       0    95.4
Permanent Ineff=
       F       F
Bank Sta=4925.1,5072.3
XS Rating Curve= 0
Exp/Cntr=.3,.1

Type RM Length L Ch R = 1 ,4676.2  ,429.1,436,434.8
BEGIN DESCRIPTION:
Cross Section 4676.2
END DESCRIPTION:
XS GIS Cut Line= 6
      3100695.05     13917460.72      3100695.02     13917460.69
      3100137.65     13916903.32      3099763.48     13916696.75
      3099603.67     13916595.41      3098738.39     13916591.51
#Sta/Elev= 30
  3956.3      95  4006.3    94.7  4026.3      95  4046.3      94  4066.3    93.7
  4084.1   94.06  4106.3    94.5  4166.3    93.8  4176.3    92.5  4196.3    91.8
  4306.3    93.8  4436.3    92.1  4696.3    91.1    4900   90.86  4911.2    90.9
  4925.1   91.81  4948.5   84.23  4982.3   76.34  4984.2   74.95  4986.9   73.78
  4998.2   73.64  5011.8   73.67  5018.4   75.86  5051.2   84.91  5072.3   92.48
  5085.1   91.58    5100   91.82    5172    91.3  5361.2    92.7  6226.5      96
#Mann= 7 , 1 , 0
  3956.3      .2       0  4084.1     .14       0    4900     .07       0
  4925.1     .04       0  5072.3     .07       0    5100     .14       0
  6226.5      .2       0
#XS Ineff= 2 , 0
       0  4306.3      95               0
Permanent Ineff=
       F       F
Bank Sta=4925.1,5072.3
XS Rating Curve= 0
Exp/Cntr=.3,.1

Type RM Length L Ch R = 1 ,4240.2  ,325.1,309.4,297.9
BEGIN DESCRIPTION:
Cross Section 4240.2-Interpolated
END DESCRIPTION:
XS GIS Cut Line= 6
       3101406.8     13917327.77      3101114.17     13917125.32
      3100196.27      13916452.2      3099844.41     13916268.62
      3099553.74     13916207.42      3098514.12     13916135.61
#Sta/Elev= 30
  3508.6    95.9  3792.3   95.11  3944.4    95.1  4204.4    91.8  4494.4    93.1
  4709.4    92.4  4719.3   91.15  4764.4    80.8  4779.4    79.4  4824.4    79.3
  4839.4    80.9  4874.4    87.9  4894.3    89.8  4929.4    88.7  4939.4      88
 4966.35   81.55 4985.95   73.54 4998.55   73.45 5017.65   74.74 5052.35   83.71
 5075.65   88.28 5076.65   91.19    5100   89.75  5255.5   91.24  5423.6   92.23
  6436.6    95.7  6492.3    94.3  6561.6    93.9  6616.6    96.2  6738.7    96.6
#Mann= 10 , 1 , 0
  3508.6      .2       0  3792.3      .1       0  4719.3     .99       0
  4894.3     .07       0  4929.4     .04       0 5076.65     .07       0
    5100     .14       0  5255.5      .1       0  5423.6     .14       0
  6492.3      .2       0
#XS Ineff= 2 , 0
       0  4894.3    89.8               0
Permanent Ineff=
       F       F
Bank Sta=4929.4,5076.65
XS Rating Curve= 0
Exp/Cntr=.3,.1

Type RM Length L Ch R = 1 ,3930.8  ,168.6,151.7,147.5
BEGIN DESCRIPTION:
Cross Section 3930.8-Interpolated
END DESCRIPTION:
XS GIS Cut Line= 5
      3101280.04     13916773.23      3100441.37     13916215.68
      3100188.07     13916123.12      3099428.16     13915962.37
      3098918.18      13915967.1
#Sta/Elev= 30
  3881.8    97.4  3891.8    96.7  3941.8    96.9  4061.8    93.5  4111.8    93.6
  4221.8    91.8  4251.8    92.1  4281.8    91.1  4321.8    91.7  4341.8    91.2
  4431.8    92.6  4461.8    92.1  4581.8    93.1  4791.8    92.2  4821.8    92.6
  4908.8    92.6 4936.05   91.33 4966.35   81.42 4985.95   73.41 4998.55   73.32
 5010.45   73.63 5017.65   74.61 5052.35   83.58 5075.65   88.15 5076.65   91.06
  5108.8    92.4  5158.5    91.6  5935.3    94.7  6425.3    95.9  6445.3    96.4
#Mann= 3 , 1 , 0
  3881.8      .1       0 4936.05     .04       0 5076.65     .14       0
#XS Ineff= 2 , 0
       0  4431.8    92.6               0
Permanent Ineff=
       F       F
Bank Sta=4936.05,5076.65
XS Rating Curve= 0
Exp/Cntr=.5,.3

Type RM Length L Ch R = 1 ,3779.1  ,11.2,11.2,11.2
BEGIN DESCRIPTION:
Upstream Section of Bridge/Culvert/Weir
END DESCRIPTION:
XS GIS Cut Line= 6
       3101216.9      13916198.8       3101198.5     13916199.58
      3100590.17     13916062.33      3099977.12     13915902.68
      3099788.41     13915879.26      3099453.68     13915889.78
#Sta/Elev= 30
  4152.3    95.4  4171.7    94.4  4201.7    91.7  4271.7    91.5  4301.7    90.6
  4451.7    90.4  4501.7    91.1  4682.5    89.9 4728.75   91.31 4771.15   91.26
 4797.25   92.14 4826.25   91.88 4879.35   92.67    4900   92.16 4936.05   91.26
 4966.35   81.35 4977.75   74.53 4982.35   74.52 4985.95   73.34 4998.55   73.25
 5010.45   73.56 5017.65   74.54 5052.35   83.51 5075.45   88.08 5076.65   90.99
    5100   91.09  5255.5   90.94  5423.6   91.72  5573.1    93.1  5953.1    94.1
#Mann= 7 , 1 , 0
  4152.3      .1       0    4900     .07       0 4936.05     .04       0
 5076.65     .07       0    5100     .14       0  5255.5      .1       0
  5423.6     .14       0
#XS Ineff= 2 , 0
       0  4935.7    89.5  5076.5       0    91.5
Permanent Ineff=
       F       F
Bank Sta=4936.05,5076.65
XS Rating Curve= 0
Exp/Cntr=.5,.3

Type RM Length L Ch R = 3 ,3768.6  ,,,
BEGIN DESCRIPTION:
15" PIPELINE U/S OF RANKIN ROAD
END DESCRIPTION:
Bridge Culvert--1,0,-1,-1, 0
Deck Dist Width WeirC Skew NumUp NumDn MinLoCord MaxHiCord MaxSubmerge Is_Ogee
10,1,2.6,0, 53, 53, , , .95, 0, 1,1,,
  4152.3  4171.7  4201.7  4231.7  4271.7  4301.7  4381.7  4391.7  4431.7  4451.7
  4501.7  4551.7  4611.7  4632.5  4682.5 4728.75 4771.15 4797.25 4826.25 4879.35
    4900 4936.05 4942.65 4947.26 4947.35 4966.35 4977.75 4982.35 4985.95 4998.55
 5010.45 5017.65 5027.55 5052.35 5075.34 5075.45 5075.55 5075.65 5076.65    5100
 5142.95 5186.95 5230.15  5255.5 5275.95  5382.8  5422.8  5423.6  5432.8  5452.8
  5573.1  5933.1  5953.1
    95.4    94.4    91.7    91.2    91.5    90.6    90.4    90.9    90.7    90.4
    91.1    90.9    90.1    90.5    89.9   91.31   91.26   92.14   91.88   92.67
   92.16   91.26   89.11    88.9    88.9      89   89.06   89.08    89.1   89.16
   89.22   89.26   89.31   89.43   89.55   89.55   89.55   88.57   90.99   91.09
   91.27   91.28      91   90.94    90.9    91.8    91.7   91.72      92    91.8
    93.1    94.2    94.1
    95.4    94.4    91.7    91.2    91.5    90.6    90.4    90.9    90.7    90.4
    91.1    90.9    90.1    90.5    89.9   91.31   91.26   92.14   91.88   92.67
   92.16   91.26    89.1   87.59   87.65   87.75   87.81   87.83   87.85   87.91
   87.97   88.01   88.06   88.18    88.3   88.08   88.32   88.57   90.99   91.09
   91.27   91.28      91   90.94    90.9    91.8    91.7   91.72      92    91.8
    93.1    94.2    94.1
  4152.3  4171.7  4201.7  4231.7  4271.7  4301.7  4381.7  4391.7  4431.7  4451.7
  4501.7  4551.7  4611.7  4632.5  4682.5 4728.75 4771.15 4797.25 4826.25 4879.35
    4900 4936.05 4942.65 4947.26 4947.35 4966.35 4977.75 4982.35 4985.95 4998.55
 5010.45 5017.65 5027.55 5052.35 5075.34 5075.45 5075.55 5075.65 5076.65    5100
 5142.95 5186.95 5230.15  5255.5 5275.95  5382.8  5422.8  5423.6  5432.8  5452.8
  5573.1  5933.1  5953.1
    95.4    94.4    91.7    91.2    91.5    90.6    90.4    90.9    90.7    90.4
    91.1    90.9    90.1    90.5    89.9   91.31   91.26   92.14   91.88   92.67
   92.16   91.26   89.11    88.9    88.9      89   89.06   89.08    89.1   89.16
   89.22   89.26   89.31   89.43   89.55   89.55   89.55   88.57   90.99   91.09
   91.27   91.28      91   90.94    90.9    91.8    91.7   91.72      92    91.8
    93.1    94.2    94.1
    95.4    94.4    91.7    91.2    91.5    90.6    90.4    90.9    90.7    90.4
    91.1    90.9    90.1    90.5    89.9   91.31   91.26   92.14   91.88   92.67
   92.16   91.26    89.1   87.59   87.65   87.75   87.81   87.83   87.85   87.91
   87.97   88.01   88.06   88.18    88.3   88.08   88.32   88.57   90.99   91.09
   91.27   91.28      91   90.94    90.9    91.8    91.7   91.72      92    91.8
    93.1    94.2    94.1
Pier Skew, UpSta & Num, DnSta & Num=  ,4977.8, 2 ,4977.8, 2 , 0 , 0 , 0 ,,
     1.4     1.4
   73.53   88.81
     1.4     1.4
   73.53   88.81
Pier Skew, UpSta & Num, DnSta & Num=  ,5027.6, 2 ,5027.6, 2 , 0 , 0 , 0 ,,
     1.4     1.4
   75.95   89.06
     1.4     1.4
   75.95   89.06
BR Coef= 1 , 1 , 0 ,1.25, 0 ,,,.8,0,2,0,
WSPro=,,,, 1 ,,,, 0 ,,,, 0 ,,,,-1 ,-1 ,-1 , 0 , 0 , 0 , 0 , 0
BR U #Sta/Elev= 53
  4152.3    95.4  4171.7    94.4  4201.7    91.7  4231.7    91.2  4271.7    91.5
  4301.7    90.6  4381.7    90.4  4391.7    90.9  4431.7    90.7  4451.7    90.4
  4501.7    91.1  4551.7    90.9  4611.7    90.1  4632.5    90.5  4682.5    89.9
 4728.75   91.31 4771.15   91.26 4797.25   92.14 4826.25   91.88 4879.35   92.67
    4900   92.16 4936.05   91.26 4942.65    89.1 4947.26   87.59 4947.35   87.56
 4966.35   81.35 4977.75   74.53 4982.35   74.52 4985.95   73.34 4998.55   73.25
 5010.45   73.56 5017.65   74.54 5027.55   77.13 5052.35   83.51 5075.34   88.06
 5075.45   88.08 5075.55   88.32 5075.65   88.57 5076.65   90.99    5100   91.09
 5142.95   91.27 5186.95   91.28 5230.15      91  5255.5   90.94 5275.95    90.9
  5382.8    91.8  5422.8    91.7  5423.6   91.72  5432.8      92  5452.8    91.8
  5573.1    93.1  5933.1    94.2  5953.1    94.1
BR U #Mann= 7
  4152.3      .1    4900     .07 4936.05     .04 5076.65     .07    5100     .14
  5255.5      .1  5423.6     .14
BR U Banks=4936.05,5076.65
BR D #Sta/Elev= 53
  4152.3    95.4  4171.7    94.4  4201.7    91.7  4231.7    91.2  4271.7    91.5
  4301.7    90.6  4381.7    90.4  4391.7    90.9  4431.7    90.7  4451.7    90.4
  4501.7    91.1  4551.7    90.9  4611.7    90.1  4632.5    90.5  4682.5    89.9
 4728.75   91.31 4771.15   91.26 4797.25   92.14 4826.25   91.88 4879.35   92.67
    4900   92.16 4936.05   91.26 4942.65    89.1 4947.26   87.59 4947.35   87.56
 4966.35   81.35 4977.75   74.53 4982.35   74.52 4985.95   73.34 4998.55   73.25
 5010.45   73.56 5017.65   74.54 5027.55   77.13 5052.35   83.51 5075.34   88.06
 5075.45   88.08 5075.55   88.32 5075.65   88.57 5076.65   90.99    5100   91.09
 5142.95   91.27 5186.95   91.28 5230.15      91  5255.5   90.94 5275.95    90.9
  5382.8    91.8  5422.8    91.7  5423.6   91.72  5432.8      92  5452.8    91.8
  5573.1    93.1  5933.1    94.2  5953.1    94.1
BR D #Mann= 7
  4152.3      .1    4900     .07 4936.05     .04 5076.65     .07    5100     .14
  5255.5      .1  5423.6     .14
BR D Banks=4936.05,5076.65
BC Design=,, 0 ,, 0 ,,,,,,

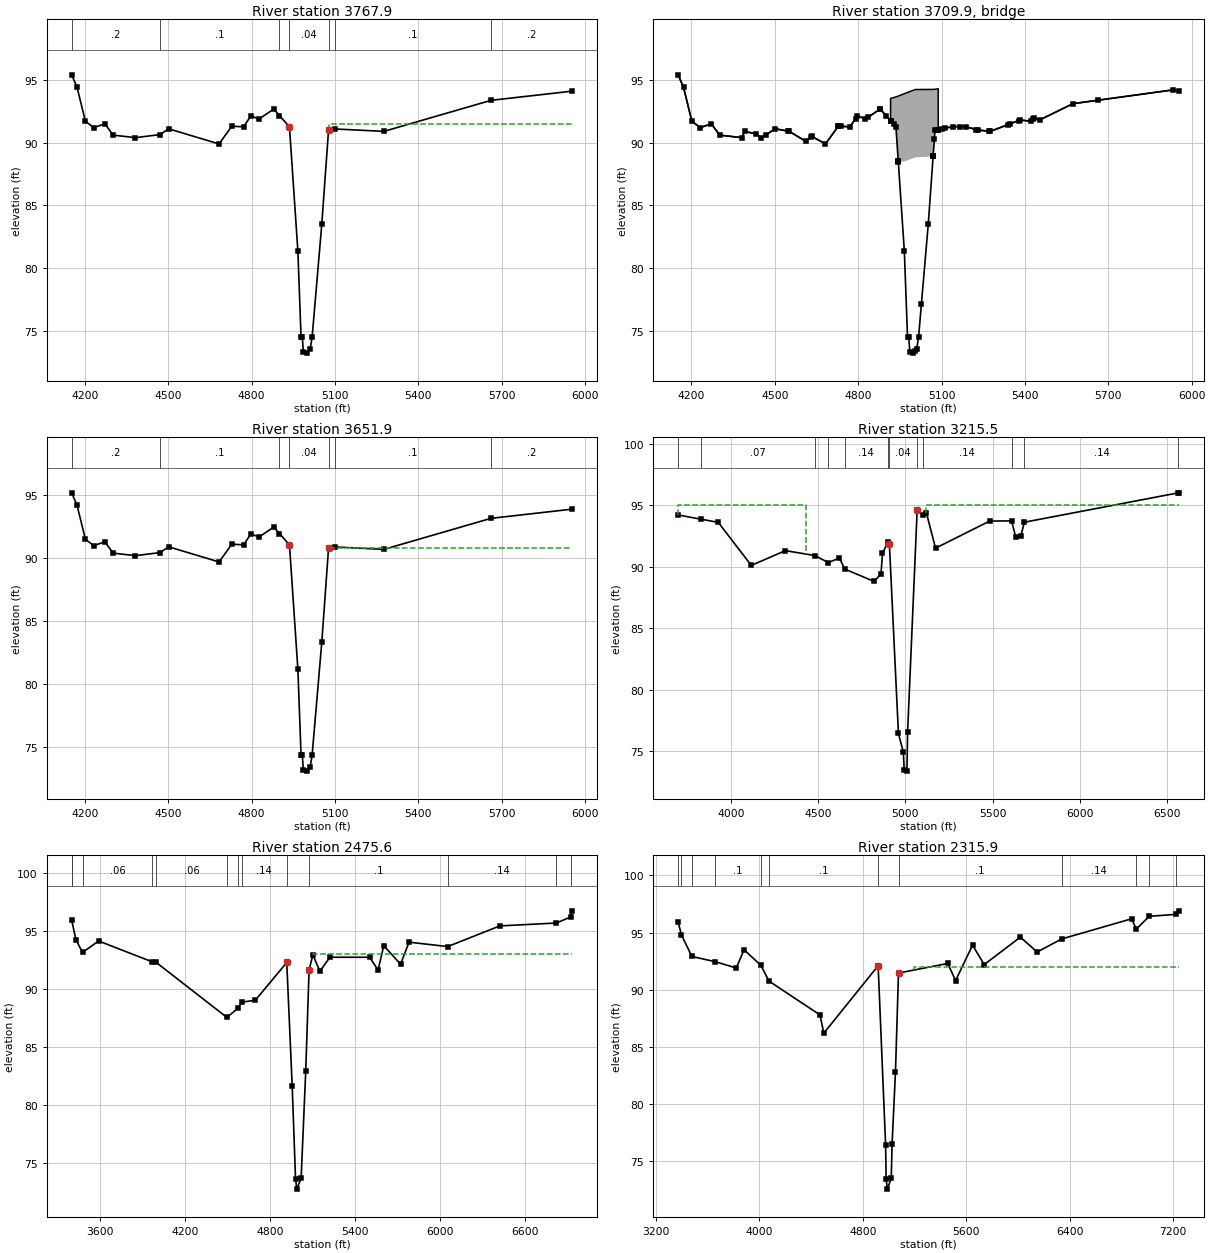
Type RM Length L Ch R = 1 ,3767.9  ,116,116,116
BEGIN DESCRIPTION:
Upstream Section of Bridge/Culvert/Weir
END DESCRIPTION:
XS GIS Cut Line= 6
      3101199.07     13916242.85      3101180.68     13916243.63
      3100572.35     13916106.38       3099959.3     13915946.73
      3099770.59     13915923.31      3099435.85     13915933.83
#Sta/Elev= 30
  4152.3    95.4  4171.7    94.4  4201.7    91.7  4231.7    91.2  4271.7    91.5
  4301.7    90.6  4381.7    90.4  4468.9   90.64  4501.7    91.1  4682.5    89.9
  4728.7   91.31  4771.1   91.26  4797.2   92.14  4826.2   91.88  4879.3   92.67
    4900   92.16    4936   91.26  4966.3   81.35  4977.7   74.53  4982.3   74.52
  4985.9   73.34  4998.5   73.25  5010.4   73.56  5017.6   74.54  5052.3   83.51
  5076.6   90.99    5100   91.09  5275.9    90.9  5661.4   93.37  5953.1    94.1
#Mann= 7 , 1 , 0
  4152.3      .2       0  4468.9      .1       0    4900     .07       0
    4936     .04       0  5076.6     .07       0    5100      .1       0
  5661.4      .2       0
#XS Ineff= 2 , 0
       0    4936    89.5    5077       0    91.5
Permanent Ineff=
       F       F
Bank Sta=4936,5076.6
XS Rating Curve= 0
Exp/Cntr=.5,.3

Type RM Length L Ch R = 3 ,3709.9  ,,,
BEGIN DESCRIPTION:
RANKIN ROAD
Structure ID: P45-03
END DESCRIPTION:
Bridge Culvert--1,0,-1,-1, 0
Deck Dist Width WeirC Skew NumUp NumDn MinLoCord MaxHiCord MaxSubmerge Is_Ogee
10,96,2.6,0, 41, 41, , , .95, 0, 1,1,,
  4152.3  4171.7  4201.7  4231.7  4271.7  4301.7  4381.7  4391.7  4431.7  4451.7
  4501.7  4551.7  4611.7  4632.5  4682.5  4728.7  4771.1  4797.2  4826.2  4879.5
 4916.69  4916.8    4936  4944.5  4966.3  5005.7  5069.8  5076.6  5088.1 5088.21
  5142.9  5186.9  5230.1  5275.9  5382.8  5422.8  5432.8  5452.8  5573.1  5933.1
  5953.1
    95.4    94.4    91.7    91.2    91.5    90.6    90.4    90.9    90.7    90.4
   91.11   90.91   90.11   90.51   89.91   91.32   91.27   92.15   91.89   92.68
   91.75   93.52   93.64   93.71    93.9   94.23   94.24   94.25   94.29   91.09
   91.28   91.29   91.01   90.91   91.81   91.71   92.01   91.81   93.11    94.2
    94.1
    95.4    94.4    91.7    91.2    91.5    90.6    90.4    90.9    90.7    90.4
    91.1    90.9    90.1    90.5    89.9   91.31   91.26   92.14   91.88   92.67
   91.74   91.74   91.26   88.48    88.5   88.83    88.9   90.99   91.04   91.04
   91.27   91.28      91    90.9    91.8    91.7      92    91.8    93.1    94.2
    94.1
  4152.3  4171.7  4201.7  4231.7  4271.7  4301.7  4381.7  4391.7  4431.7  4451.7
  4501.7  4551.7  4611.7  4632.5  4682.5  4728.7  4771.1  4797.2  4826.2  4879.5
 4916.69  4916.8    4936  4944.5  4966.3  5005.7  5069.8  5076.6  5088.1 5088.21
  5142.9  5186.9  5230.1  5275.9  5382.8  5422.8  5432.8  5452.8  5573.1  5933.1
  5953.1
    95.4    94.4    91.7    91.2    91.5    90.6    90.4    90.9    90.7    90.4
   91.11   90.91   90.11   90.51   89.91   91.32   91.27   92.15   91.89   92.68
   91.75   93.52   93.64   93.71    93.9   94.23   94.24   94.25   94.29   91.09
   91.28   91.29   91.01   90.91   91.81   91.71   92.01   91.81   93.11    94.2
    94.1
   95.19   94.19   91.49   90.99   91.29   90.39   90.19   90.69   90.49   90.19
   90.89   90.69   89.89   90.29   89.69    91.1   91.05   91.93   91.67   92.46
   91.53   91.53   91.05   88.27   88.29   88.62   88.69   90.78   90.83   90.83
   91.06   91.07   90.79   90.69   91.59   91.49   91.79   91.59   92.89   93.99
   93.89
BR Coef= 1 , 1 , 0 ,1.25, 0 ,,,.8,-1,2,0,
WSPro=,,,, 1 ,,,, 0 ,,,, 0 ,,,,-1 ,-1 ,-1 , 0 , 0 , 0 , 0 , 0
BR U #Sta/Elev= 76
  4152.3    95.4  4171.7    94.4  4201.7    91.7  4231.7    91.2  4271.7    91.5
  4301.7    90.6  4381.7    90.4  4391.7    90.9  4431.7    90.7  4451.7    90.4
  4468.9   90.64  4501.7    91.1  4548.9   90.91  4551.7    90.9  4611.7    90.1
  4628.9   90.43  4632.5    90.5  4682.5    89.9  4728.7   91.31  4728.9   91.31
  4737.3    91.3  4771.1   91.26  4790.6   91.92  4797.2   92.14  4826.2   91.88
  4835.6   92.02  4879.3   92.67  4879.5   92.67    4900   92.16 4916.69   91.74
  4916.8   91.74 4916.91   91.73  4927.3   91.48    4936   91.26 4944.21   88.57
  4944.4   88.51  4944.5   88.48  4966.3   81.35  4977.7   74.53  4982.3   74.52
  4985.9   73.34  4998.5   73.25  5005.7   73.44  5010.4   73.56  5017.6   74.54
  5027.5   77.13  5052.3   83.51  5069.8    88.9 5069.89   88.92    5070   88.96
  5074.3   90.28  5076.6   90.99 5087.99   91.04  5088.1   91.04 5088.21   91.04
    5100   91.09  5113.5   91.15  5142.9   91.27  5166.8   91.28  5186.9   91.28
  5223.5   91.04  5230.1      91  5271.4   90.91  5275.9    90.9  5337.9   91.42
  5347.9   91.51  5377.9   91.76  5382.8    91.8  5422.8    91.7  5428.1   91.86
  5432.8      92  5452.8    91.8  5573.1    93.1  5661.4   93.37  5933.1    94.2
  5953.1    94.1
BR U #Mann= 7
  4152.3      .2  4468.9      .1    4900     .07    4936     .04  5076.6     .07
    5100      .1  5661.4      .2
BR U Banks=4936,5076.6
BR D #Sta/Elev= 76
  4152.3   95.19  4171.7   94.19  4201.7   91.49  4231.7   90.99  4271.7   91.29
  4301.7   90.39  4381.7   90.19  4391.7   90.69  4431.7   90.49  4451.7   90.19
  4468.9   90.43  4501.7   90.89  4548.9    90.7  4551.7   90.69  4611.7   89.89
  4628.9   90.22  4632.5   90.29  4682.5   89.69  4728.7    91.1  4728.9    91.1
  4737.3   91.09  4771.1   91.05  4790.6   91.71  4797.2   91.93  4826.2   91.67
  4835.6   91.81  4879.3   92.46  4879.5   92.46    4900   91.95 4916.69   91.53
  4916.8   91.53 4916.91   91.52  4927.3   91.27    4936   91.05 4944.21   88.36
  4944.4    88.3  4944.5   88.27  4966.3   81.14  4977.7   74.32  4982.3   74.31
  4985.9   73.13  4998.5   73.04  5005.7   73.23  5010.4   73.35  5017.6   74.33
  5027.5   76.92  5052.3    83.3  5069.8   88.69 5069.89   88.71    5070   88.75
  5074.3   90.07  5076.6   90.78 5087.99   90.83  5088.1   90.83 5088.21   90.83
    5100   90.88  5113.5   90.94  5142.9   91.06  5166.8   91.07  5186.9   91.07
  5223.5   90.83  5230.1   90.79  5271.4    90.7  5275.9   90.69  5337.9   91.21
  5347.9    91.3  5377.9   91.55  5382.8   91.59  5422.8   91.49  5428.1   91.65
  5432.8   91.79  5452.8   91.59  5573.1   92.89  5661.4   93.16  5933.1   93.99
  5953.1   93.89
BR D #Mann= 7
  4152.3      .2  4468.9      .1    4900     .07    4936     .04  5076.6     .07
    5100      .1  5661.4      .2
BR D Banks=4936,5076.6
BC Design=,, 0 ,, 0 ,,,,,,

Type RM Length L Ch R = 1 ,3651.9  ,436.4,436.4,436.4
BEGIN DESCRIPTION:
Downstream Section of Bridge/Culvert/Weir
END DESCRIPTION:
XS GIS Cut Line= 6
      3101241.24     13916134.79      3101222.84     13916135.57
      3100614.51     13915998.32      3100001.46     13915838.67
      3099812.75     13915815.25      3099478.02     13915825.77
#Sta/Elev= 30
  4152.3    95.2  4171.7    94.2  4201.7    91.5  4231.7      91  4271.7    91.3
  4301.7    90.4  4381.7    90.2  4468.9   90.44  4501.7    90.9  4682.5    89.7
  4728.7   91.11  4771.1   91.06  4797.2   91.94  4826.2   91.68  4879.3   92.47
    4900   91.96    4936   91.06  4966.3   81.15  4977.7   74.33  4982.3   74.32
  4985.9   73.14  4998.5   73.05  5010.4   73.36  5017.6   74.34  5052.3   83.31
  5076.6   90.79    5100   90.89  5275.9    90.7  5661.4   93.17  5953.1    93.9
#Mann= 7 , 1 , 0
  4152.3      .2       0  4468.9      .1       0    4900     .07       0
    4936     .04       0  5076.6     .07       0    5100      .1       0
  5661.4      .2       0
#XS Ineff= 2 , 0
       0    4936    89.5    5077       0    90.8
Permanent Ineff=
       F       F
Bank Sta=4936,5076.6
XS Rating Curve= 0
Exp/Cntr=.5,.3

Type RM Length L Ch R = 1 ,3215.5  ,736.9,739.9,744.2
BEGIN DESCRIPTION:
Cross Section 3215.5
END DESCRIPTION:
XS GIS Cut Line= 6
       3101855.9     13915780.42      3101380.68     13915678.96
      3100846.73     13915609.55      3100424.91     13915444.03
      3099586.61     13915193.07      3099067.79     13915227.04
#Sta/Elev= 30
  3695.6    94.2  3828.3   93.85  3925.6    93.6  4115.6    90.1  4311.5    91.3
  4480.3    90.9  4557.5   90.33  4621.5    90.7  4651.4    89.8  4819.9    88.8
  4859.9    89.4  4868.5   91.07  4900.4   92.02  4908.1   91.84    4960   76.43
  4988.3   74.91  4993.4   73.43  5008.9   73.37  5012.7   76.58  5067.6   94.62
    5100    94.2  5119.9    94.4  5173.1    91.5  5483.1    93.7  5609.8   93.72
  5633.1    92.4  5663.1    92.5  5682.7   93.61  6567.4      96  6568.1      96
#Mann= 12 , 1 , 0
  3695.6      .1       0  3828.3     .07       0  4480.3      .1       0
  4557.5     .06       0  4651.4     .14       0  4900.4     .07       0
  4908.1     .04       0  5067.6     .07       0    5100     .14       0
  5609.8      .1       0  5682.7     .14       0  6567.4      .1       0
#XS Ineff= 2 , 0
       0    4430      95    5120       0      95
Permanent Ineff=
       F       F
Bank Sta=4908.1,5067.6
XS Rating Curve= 0
Exp/Cntr=.3,.1

Type RM Length L Ch R = 1 ,2475.6  ,134.4,159.7,149.8
BEGIN DESCRIPTION:
Cross Section 2475.6-Interpolated
END DESCRIPTION:
XS GIS Cut Line= 6
      3102162.14     13915711.27      3101573.97     13915175.83
      3100927.09     13914850.79      3100779.97     13914783.91
       3100267.2     13914562.92      3098987.48     13914725.53
#Sta/Elev= 30
  3401.5    95.9  3431.5    94.2  3478.1   93.12  3591.5    94.1  3970.9    92.3
  3995.9   92.27  4495.8   87.52  4573.1   88.29  4601.5   88.83  4696.9      89
  4918.3   92.25  4956.6   81.62  4980.2   73.61  4989.2   72.72  5019.8   73.66
  5052.2   82.92  5075.8   91.61  5102.4    92.9  5152.4    91.5  5222.4    92.7
  5502.4    92.7  5562.4    91.6  5602.4    93.7  5720.8    92.1  5780.8      94
  6053.4   93.62  6420.8    95.4  6819.5   95.65  6921.1   96.17  6930.8    96.7
#Mann= 13 , 1 , 0
  3401.5      .2       0  3401.5      .1       0  3478.1     .06       0
  3970.9      .1       0  3995.9     .06       0  4495.8      .1       0
  4573.1     .06       0  4601.5     .14       0  4918.3     .04       0
  5075.8      .1       0  6053.4     .14       0  6819.5      .1       0
  6921.1     .14       0
#XS Ineff= 2 , 0
       0                    5102       0      93
Permanent Ineff=
       F       F
Bank Sta=4918.3,5075.8
XS Rating Curve= 0
Exp/Cntr=.5,.3

Type RM Length L Ch R = 1 ,2315.9  ,72.6,72.6,72.6
BEGIN DESCRIPTION:
Upstream Section of Bridge/Culvert/Weir
END DESCRIPTION:
XS GIS Cut Line= 6
      3102188.89     13915647.94      3101751.47     13915146.38
      3101469.13       13914976.      3100940.52     13914693.01
      3100410.34     13914379.16      3098769.14     13914638.47
#Sta/Elev= 30
  3370.6   95.91    3396   94.81  3476.9   92.92  3659.1   92.46  3820.6   91.91
  3880.6   93.51  4011.2   92.14    4073   90.77  4468.3   87.81  4497.6   86.21
  4918.3   92.11  4975.9   76.46  4980.2   73.47  4989.2   72.58  5019.8   73.52
    5026    76.5  5052.2   82.78  5075.8   91.47  5457.5   92.31  5517.5   90.81
  5648.9   93.91  5738.9   92.21  6018.9   94.61  6148.9   93.31  6338.3   94.45
  6878.9   96.21  6916.7   95.32  7016.3   96.43    7221    96.6  7243.2   96.91
#Mann= 12 , 1 , 0
  3370.6      .2       0    3396      .1       0  3476.9     .07       0
  3659.1      .1       0  4011.2     .07       0    4073      .1       0
  4918.3     .04       0  5075.8      .1       0  6338.3     .14       0
  6916.7      .1       0  7016.3     .14       0    7221      .2       0
#XS Ineff= 2 , 0
       0  4931.6    88.4    5195       0      92
Permanent Ineff=
       F       F
Bank Sta=4918.3,5075.8
XS Rating Curve= 0
Exp/Cntr=.5,.3

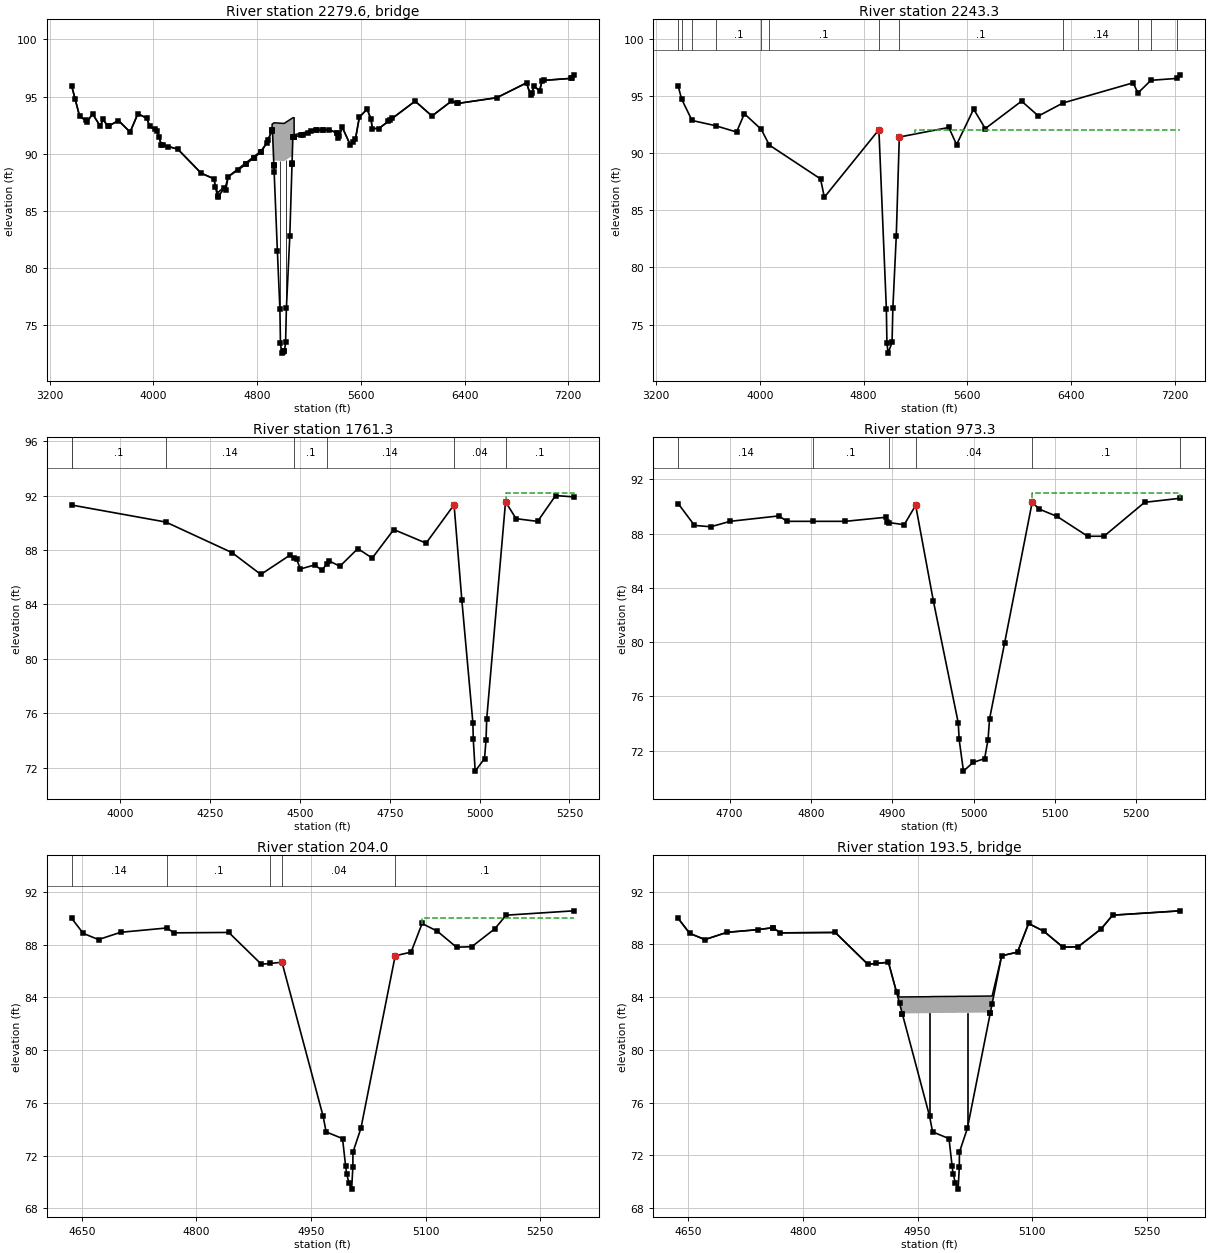
Type RM Length L Ch R = 3 ,2279.6  ,,,
BEGIN DESCRIPTION:
RUSHCREEK DRIVE
Structure ID: P45-1
END DESCRIPTION:
Bridge Culvert--1,0,-1,-1, 0
Deck Dist Width WeirC Skew NumUp NumDn MinLoCord MaxHiCord MaxSubmerge Is_Ogee
10,52.6,2.6,0, 60, 60, , , .95, 0, 1,1,,
  3370.6  3430.6  3490.6  3530.6  3590.6  3610.6  3650.6  3730.6  3820.6  3880.6
  3950.6  3970.6  4030.6  4060.6  4188.3  4368.3  4468.3  4477.6  4495.9  4547.6
  4557.6  4577.6  4829.4  4872.6 4915.59  4915.7  4918.3 4929.41  4929.5  4931.5
  5008.5 5069.49  5069.6  5075.8  5085.6 5085.71  5262.3  5357.5  5417.5  5427.5
  5457.5  5517.5  5558.9  5588.9  5648.9  5678.9  5688.9  5738.9  6018.9  6148.9
  6298.9  6348.9  6648.9  6878.9  6908.9  6938.9  6978.9  6998.9  7228.9  7243.2
    95.9    93.3    92.8    93.5    92.4      93    92.4    92.9    91.9    93.5
    93.1    92.4      92   90.81   90.41   88.31   87.81   87.11    86.6   87.09
   87.18   88.01   90.23   90.92   92.04   92.58    92.6   92.69   92.69   92.71
   92.65    93.1    93.1   93.14   93.16   91.66   92.11   92.11   91.81   91.41
   92.31   90.81   91.31   93.21   93.91   93.01   92.21   92.21    94.6    93.3
    94.6    94.4    94.9    96.2    95.1    95.9    95.5    96.4    96.6    96.9
    95.9    93.3    92.8    93.5    92.4      93    92.4    92.9    91.9    93.5
    93.1    92.4      92    90.8    90.4    88.3    87.8    87.1   86.28      87
    86.8      88   90.13   90.91   92.03   92.03    92.1   89.02   89.39   89.41
   89.35    89.8   89.18   91.46   91.48   91.48    92.1    92.1    91.8    91.4
    92.3    90.8    91.3    93.2    93.9      93    92.2    92.2    94.6    93.3
    94.6    94.4    94.9    96.2    95.1    95.9    95.5    96.4    96.6    96.9
  3370.6  3430.6  3490.6  3530.6  3590.6  3610.6  3650.6  3730.6  3820.6  3880.6
  3950.6  3970.6  4030.6  4060.6  4188.3  4368.3  4468.3  4477.6  4495.9  4547.6
  4557.6  4577.6  4829.4  4872.6 4915.59  4915.7  4918.3 4929.41  4929.5  4931.5
  5008.5 5069.49  5069.6  5075.8  5085.6 5085.71  5262.3  5357.5  5417.5  5427.5
  5457.5  5517.5  5558.9  5588.9  5648.9  5678.9  5688.9  5738.9  6018.9  6148.9
  6298.9  6348.9  6648.9  6878.9  6908.9  6938.9  6978.9  6998.9  7228.9  7243.2
    95.9    93.3    92.8    93.5    92.4      93    92.4    92.9    91.9    93.5
    93.1    92.4      92   90.81   90.41   88.31   87.81   87.11    86.6   87.09
   87.18   88.01   90.23   90.92   92.04   92.58    92.6   92.69   92.69   92.71
   92.65    93.1    93.1   93.14   93.16   91.66   92.11   92.11   91.81   91.41
   92.31   90.81   91.31   93.21   93.91   93.01   92.21   92.21    94.6    93.3
    94.6    94.4    94.9    96.2    95.1    95.9    95.5    96.4    96.6    96.9
   95.85   93.25   92.75   93.45   92.35   92.95   92.35   92.85   91.85   93.45
   93.05   92.35   91.95   90.75   90.35   88.25   87.75   87.05   86.23   86.95
   86.75   87.95   90.08   90.86   91.98   91.98   92.05   88.97   89.34   89.36
    89.3   89.75   89.13   91.41   91.43   91.43   92.05   92.05   91.75   91.35
   92.25   90.75   91.25   93.15   93.85   92.95   92.15   92.15   94.55   93.25
   94.55   94.35   94.85   96.15   95.05   95.85   95.45   96.35   96.55   96.85
Pier Skew, UpSta & Num, DnSta & Num=  ,4975.9, 2 ,4975.9, 2 , 0 , 0 , 0 ,,
     1.3     1.3
      75   90.38
     1.3     1.3
   74.95   90.33
Pier Skew, UpSta & Num, DnSta & Num=  ,5026, 2 ,5026, 2 , 0 , 0 , 0 ,,
     1.3     1.3
   75.18   90.48
     1.3     1.3
   75.13   90.43
BR Coef= 1 , 1 , 0 ,1.25, 0 ,,,.8,-1,2,0,
WSPro=,,,, 1 ,,,, 0 ,,,, 0 ,,,,-1 ,-1 ,-1 , 0 , 0 , 0 , 0 , 0
BR U #Sta/Elev= 106
  3370.6    95.9    3396    94.8  3430.6    93.3  3476.9   92.91  3490.6    92.8
  3530.6    93.5  3590.6    92.4  3610.6      93  3650.6    92.4  3659.1   92.45
  3730.6    92.9  3820.6    91.9  3880.6    93.5  3950.6    93.1  3970.6    92.4
  4011.2   92.13  4030.6      92  4043.5   91.48  4060.6    90.8    4073   90.76
  4113.5   90.63  4188.3    90.4  4368.3    88.3  4468.3    87.8  4477.6    87.1
  4495.9   86.28  4497.6    86.2  4547.6      87  4557.6    86.8  4577.6      88
  4654.8    88.6  4714.7   89.07  4714.8   89.07  4772.8   89.66  4773.4   89.66
  4828.5   90.11  4829.4   90.13  4872.6   90.91  4885.4   91.24 4915.59   92.03
  4915.7   92.03 4915.81   92.04  4918.3    92.1 4929.41   89.02  4929.5   88.99
  4929.6   88.96  4931.5   88.44  4956.6   81.47  4975.9   76.45  4980.2   73.46
  4989.2   72.57  5000.8   72.71  5008.5   72.72  5011.2   72.73  5019.8   73.51
    5026   76.49  5052.2   82.77  5069.4    89.1 5069.49   89.14  5069.6   89.18
  5075.8   91.46  5077.9   91.46 5085.49   91.48  5085.6   91.48 5085.71   91.48
  5135.7    91.6    5155   91.64  5194.3   91.85  5218.6   91.98  5251.3   92.07
  5262.3    92.1  5304.8   92.08  5306.7   92.08  5357.5    92.1  5415.5   91.81
  5417.5    91.8  5427.5    91.4  5432.5   91.55  5457.5    92.3  5517.5    90.8
  5538.9      91  5558.9    91.3  5588.9    93.2  5648.9    93.9  5678.9      93
  5688.9    92.2  5738.9    92.2  5812.5   92.83  5822.5   92.92  5843.8    93.1
  6018.9    94.6  6148.9    93.3  6298.9    94.6  6338.3   94.44  6348.9    94.4
  6648.9    94.9  6878.9    96.2  6908.9    95.1  6916.7   95.31  6938.9    95.9
  6978.9    95.5  6998.9    96.4  7016.3   96.42    7221   96.59  7228.9    96.6
  7243.2    96.9
BR U #Mann= 12
  3370.6      .2    3396      .1  3476.9     .07  3659.1      .1  4011.2     .07
    4073      .1  4918.3     .04  5075.8      .1  6338.3     .14  6916.7      .1
  7016.3     .14    7221      .2
BR U Banks=4918.3,5075.8
BR D #Sta/Elev= 106
  3370.6   95.85    3396   94.75  3430.6   93.25  3476.9   92.86  3490.6   92.75
  3530.6   93.45  3590.6   92.35  3610.6   92.95  3650.6   92.35  3659.1    92.4
  3730.6   92.85  3820.6   91.85  3880.6   93.45  3950.6   93.05  3970.6   92.35
  4011.2   92.08  4030.6   91.95  4043.5   91.43  4060.6   90.75    4073   90.71
  4113.5   90.58  4188.3   90.35  4368.3   88.25  4468.3   87.75  4477.6   87.05
  4495.9   86.23  4497.6   86.15  4547.6   86.95  4557.6   86.75  4577.6   87.95
  4654.8   88.55  4714.7   89.02  4714.8   89.02  4772.8   89.61  4773.4   89.61
  4828.5   90.06  4829.4   90.08  4872.6   90.86  4885.4   91.19 4915.59   91.98
  4915.7   91.98 4915.81   91.99  4918.3   92.05 4929.41   88.97  4929.5   88.94
  4929.6   88.91  4931.5   88.39  4956.6   81.42  4975.9    76.4  4980.2   73.41
  4989.2   72.52  5000.8   72.66  5008.5   72.67  5011.2   72.68  5019.8   73.46
    5026   76.44  5052.2   82.72  5069.4   89.05 5069.49   89.09  5069.6   89.13
  5075.8   91.41  5077.9   91.41 5085.49   91.43  5085.6   91.43 5085.71   91.43
  5135.7   91.55    5155   91.59  5194.3    91.8  5218.6   91.93  5251.3   92.02
  5262.3   92.05  5304.8   92.03  5306.7   92.03  5357.5   92.05  5415.5   91.76
  5417.5   91.75  5427.5   91.35  5432.5    91.5  5457.5   92.25  5517.5   90.75
  5538.9   90.95  5558.9   91.25  5588.9   93.15  5648.9   93.85  5678.9   92.95
  5688.9   92.15  5738.9   92.15  5812.5   92.78  5822.5   92.87  5843.8   93.05
  6018.9   94.55  6148.9   93.25  6298.9   94.55  6338.3   94.39  6348.9   94.35
  6648.9   94.85  6878.9   96.15  6908.9   95.05  6916.7   95.26  6938.9   95.85
  6978.9   95.45  6998.9   96.35  7016.3   96.37    7221   96.54  7228.9   96.55
  7243.2   96.85
BR D #Mann= 12
  3370.6      .2    3396      .1  3476.9     .07  3659.1      .1  4011.2     .07
    4073      .1  4918.3     .04  5075.8      .1  6338.3     .14  6916.7      .1
  7016.3     .14    7221      .2
BR D Banks=4918.3,5075.8
BC Design=,, 0 ,, 0 ,,,,,,

Type RM Length L Ch R = 1 ,2243.3  ,482,482,482
BEGIN DESCRIPTION:
Downstream Section of Bridge/Culvert/Weir
END DESCRIPTION:
XS GIS Cut Line= 6
      3102214.88     13915580.16      3101777.47      13915078.6
      3101495.13     13914908.22      3100966.52     13914625.23
      3100436.34     13914311.38      3098795.14     13914570.68
#Sta/Elev= 30
  3370.6   95.83    3396   94.73  3476.9   92.84  3659.1   92.38  3820.6   91.83
  3880.6   93.43  4011.2   92.06    4073   90.69  4468.3   87.73  4497.6   86.13
  4918.3   92.03  4975.9   76.38  4980.2   73.39  4989.2    72.5  5019.8   73.44
    5026   76.42  5052.2    82.7  5075.8   91.39  5457.5   92.23  5517.5   90.73
  5648.9   93.83  5738.9   92.13  6018.9   94.53  6148.9   93.23  6338.3   94.37
  6878.9   96.13  6916.7   95.24  7016.3   96.35    7221   96.52  7243.2   96.83
#Mann= 12 , 1 , 0
  3370.6      .2       0    3396      .1       0  3476.9     .07       0
  3659.1      .1       0  4011.2     .07       0    4073      .1       0
  4918.3     .04       0  5075.8      .1       0  6338.3     .14       0
  6916.7      .1       0  7016.3     .14       0    7221      .2       0
#XS Ineff= 2 , 0
       0  4931.6    88.4    5195       0      92
Permanent Ineff=
       F       F
Bank Sta=4918.3,5075.8
XS Rating Curve= 0
Exp/Cntr=.5,.3

Type RM Length L Ch R = 1 ,1761.3  ,779.5,788,776.2
BEGIN DESCRIPTION:
Cross Section 1761.3-Interpolated
END DESCRIPTION:
XS GIS Cut Line= 4
      3101839.91     13914876.41      3101736.27     13914442.41
      3101129.47     13914157.45       3100863.6     13914067.03
#Sta/Elev= 30
  3864.8    91.3  4126.8   90.05    4311    87.8    4391    86.2    4471    87.6
  4483.1   87.42    4491    87.3    4501    86.6    4541    86.9    4561    86.5
    4574   86.96    4581    87.2    4611    86.8    4661    88.1    4701    87.4
    4761    89.5    4851    88.5  4928.8   91.32  4950.5    84.3  4981.2   75.29
  4982.3   74.07  4987.6   71.74  5013.6   72.66  5017.8   74.05  5019.7   75.59
  5072.1   91.54  5101.4    90.3  5161.4    90.1  5211.4      92  5262.2    91.9
#Mann= 7 , 1 , 0
  3864.8      .2       0  3864.8      .1       0  4126.8     .14       0
  4483.1      .1       0    4574     .14       0  4928.8     .04       0
  5072.1      .1       0
#XS Ineff= 2 , 0
       0                    5073       0    92.2
Permanent Ineff=
       F       F
Bank Sta=4928.8,5072.1
XS Rating Curve= 0
Exp/Cntr=.3,.1

Type RM Length L Ch R = 1 ,973.3   ,769.3,769.3,769.3
BEGIN DESCRIPTION:
Cross Section 973.3
END DESCRIPTION:
XS GIS Cut Line= 5
      3101632.45     13913637.07      3101581.86     13913598.18
      3101514.17     13913473.75      3101289.91     13913393.66
      3101116.04     13913391.24
#Sta/Elev= 29
  4636.8    90.2  4656.8    88.6  4676.8    88.5  4700.6    88.9  4760.6    89.3
  4770.6    88.9    4803    88.9  4842.3    88.9  4892.3    89.2  4893.1   88.83
    4896   88.81  4914.7   88.65  4928.8   90.08  4950.5   83.06  4981.2   74.05
  4982.3   72.83  4987.6    70.5  4999.4   71.14  5013.6   71.42  5017.8   72.81
  5019.7   74.35  5038.2   79.94  5072.1    90.3  5080.8    89.8  5102.8   89.26
  5140.4    87.8  5160.4    87.8  5210.4    90.3  5254.3    90.6
#Mann= 6 , 1 , 0
  4636.8     .14       0    4803      .1       0    4896     .14       0
  4928.8     .04       0  5072.1      .1       0  5254.3      .2       0
#XS Ineff= 2 , 0
       0                  5071.3       0      91
Permanent Ineff=
       F       F
Bank Sta=4928.8,5072.1
XS Rating Curve= 0
Exp/Cntr=.5,.3

Type RM Length L Ch R = 1 ,204.0   ,21,21,21
BEGIN DESCRIPTION:
Upstream Section of Bridge/Culvert/Weir
END DESCRIPTION:
XS GIS Cut Line= 2
      3101756.74     13912997.27      3101358.24     13912474.67
#Sta/Elev= 29
  4636.8   89.98  4651.8   88.85  4671.8   88.38  4700.6   88.93  4761.2   89.26
  4770.6   88.89  4842.3   88.92 4884.94   86.51    4896   86.57 4911.94   86.66
 4965.74      75 4969.74    73.8 4991.24   73.29 4995.24   71.22 4996.54   70.64
 4999.64   69.92 5003.14   69.46 5004.74   71.13 5004.84   72.26 5015.24   74.06
 5060.14   87.15 5080.94   87.43  5095.4    89.6  5115.4   89.01  5140.4    87.8
  5160.4   87.84  5190.4   89.19  5205.4   90.23    5294   90.56
#Mann= 5 , 1 , 0
  4636.8     .14       0  4761.2      .1       0    4896     .14       0
 4911.94     .04       0 5060.14      .1       0
#XS Ineff= 2 , 0
       0    4901    86.5    5095       0      90
Permanent Ineff=
       F       F
Bank Sta=4911.94,5060.14
XS Rating Curve= 0
Exp/Cntr=.5,.3

Type RM Length L Ch R = 3 ,193.5   ,,,
BEGIN DESCRIPTION:
15" PIPELINE
END DESCRIPTION:
Bridge Culvert--1,0,-1,-1, 0
Deck Dist Width WeirC Skew NumUp NumDn MinLoCord MaxHiCord MaxSubmerge Is_Ogee
10,1,2.6,0, 38, 38, , , .95, 0, 1,1,,
  4636.8  4651.8  4671.8  4700.6  4740.6  4760.6  4761.2  4770.6  4842.3 4884.94
    4896 4911.94 4922.54 4926.44 4930.11  4930.2 4965.74 4969.74 4991.24 4995.24
 4996.54 4999.64 5003.14 5004.74 5004.84 5015.24 5045.19  5045.3 5047.64 5060.14
 5080.94  5095.4  5115.4  5140.4  5160.4  5190.4  5205.4    5294
   89.97   88.84   88.37   88.92   89.12   89.27   89.25   88.88   88.91    86.5
   86.56   86.65   84.39   84.02   84.02   84.02   84.04   84.05   84.06   84.06
   84.06   84.06   84.07   84.07   84.07   84.07   84.09   84.09   84.09   87.14
   87.42   89.59      89   87.79   87.83   89.18   90.22   90.55
   89.97   88.84   88.37   88.92   89.12   89.27   89.25   88.88   88.91    86.5
   86.56   86.65   84.38   83.55   82.75   82.77   82.79    82.8   82.81   82.81
   82.81   82.81   82.82   82.82   82.82   82.82   82.84   82.81    83.5   87.14
   87.42   89.59      89   87.79   87.83   89.18   90.22   90.55
  4636.8  4651.8  4671.8  4700.6  4740.6  4760.6  4761.2  4770.6  4842.3 4884.94
    4896 4911.94 4922.54 4926.44 4930.11  4930.2 4965.74 4969.74 4991.24 4995.24
 4996.54 4999.64 5003.14 5004.74 5004.84 5015.24 5045.19  5045.3 5047.64 5060.14
 5080.94  5095.4  5115.4  5140.4  5160.4  5190.4  5205.4    5294
   89.97   88.84   88.37   88.92   89.12   89.27   89.25   88.88   88.91    86.5
   86.56   86.65   84.39   84.02   84.02   84.02   84.04   84.05   84.06   84.06
   84.06   84.06   84.07   84.07   84.07   84.07   84.09   84.09   84.09   87.14
   87.42   89.59      89   87.79   87.83   89.18   90.22   90.55
   89.97   88.84   88.37   88.92   89.12   89.27   89.25   88.88   88.91    86.5
   86.56   86.65   84.38   83.55   82.75   82.77   82.79    82.8   82.81   82.81
   82.81   82.81   82.82   82.82   82.82   82.82   82.84   82.81    83.5   87.14
   87.42   89.59      89   87.79   87.83   89.18   90.22   90.55
Pier Skew, UpSta & Num, DnSta & Num=  ,4965.7, 2 ,4965.7, 2 , 0 , 0 , 0 ,,
       2       2
   73.69   83.79
       2       2
   73.69   83.79
Pier Skew, UpSta & Num, DnSta & Num=  ,5015.2, 2 ,5015.2, 2 , 0 , 0 , 0 ,,
       2       2
   72.88   83.82
       2       2
   72.88   83.82
BR Coef= 1 , 1 , 0 ,1.25, 0 ,,,.8,0,2,0,
WSPro=,,,, 1 ,,,, 0 ,,,, 0 ,,,,-1 ,-1 ,-1 , 0 , 0 , 0 , 0 , 0
BR U #Sta/Elev= 38
  4636.8   89.97  4651.8   88.84  4671.8   88.37  4700.6   88.92  4740.6   89.12
  4760.6   89.27  4761.2   89.25  4770.6   88.88  4842.3   88.91 4884.94    86.5
    4896   86.56 4911.94   86.65 4922.54   84.38 4926.44   83.55 4930.11   82.75
  4930.2   82.73 4965.74   74.99 4969.74   73.79 4991.24   73.28 4995.24   71.21
 4996.54   70.63 4999.64   69.91 5003.14   69.45 5004.74   71.12 5004.84   72.25
 5015.24   74.05 5045.19   82.78  5045.3   82.81 5047.64    83.5 5060.14   87.14
 5080.94   87.42  5095.4   89.59  5115.4      89  5140.4   87.79  5160.4   87.83
  5190.4   89.18  5205.4   90.22    5294   90.55
BR U #Mann= 5
  4636.8     .14  4761.2      .1    4896     .14 4911.94     .04 5060.14      .1
BR U Banks=4911.94,5060.14
BR D #Sta/Elev= 38
  4636.8   89.97  4651.8   88.84  4671.8   88.37  4700.6   88.92  4740.6   89.12
  4760.6   89.27  4761.2   89.25  4770.6   88.88  4842.3   88.91 4884.94    86.5
    4896   86.56 4911.94   86.65 4922.54   84.38 4926.44   83.55 4930.11   82.75
  4930.2   82.73 4965.74   74.99 4969.74   73.79 4991.24   73.28 4995.24   71.21
 4996.54   70.63 4999.64   69.91 5003.14   69.45 5004.74   71.12 5004.84   72.25
 5015.24   74.05 5045.19   82.78  5045.3   82.81 5047.64    83.5 5060.14   87.14
 5080.94   87.42  5095.4   89.59  5115.4      89  5140.4   87.79  5160.4   87.83
  5190.4   89.18  5205.4   90.22    5294   90.55
BR D #Mann= 5
  4636.8     .14  4761.2      .1    4896     .14 4911.94     .04 5060.14      .1
BR D Banks=4911.94,5060.14
BC Design=,, 0 ,, 0 ,,,,,,

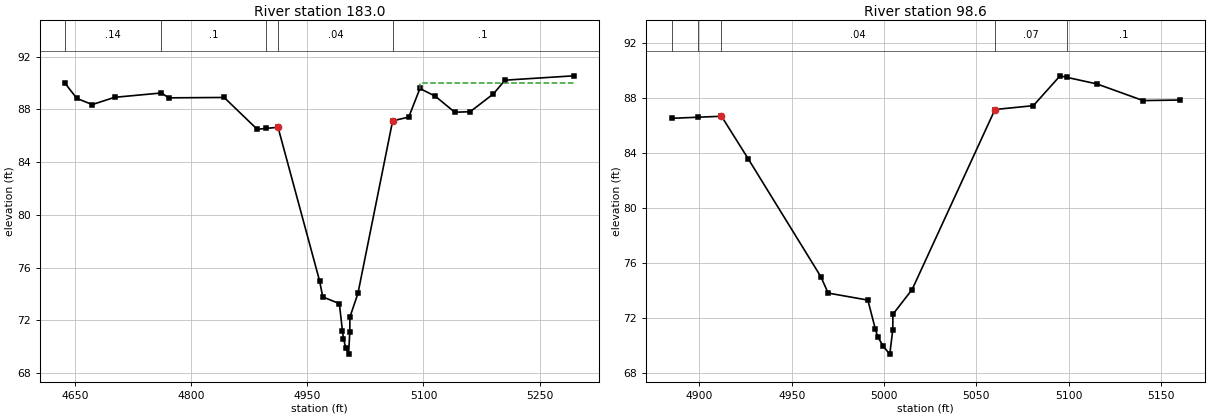
Type RM Length L Ch R = 1 ,183.0   ,84.4,84.4,84.4
BEGIN DESCRIPTION:
Downstream Section of Bridge/Culvert/Weir
END DESCRIPTION:
XS GIS Cut Line= 2
      3101775.18     13912987.22      3101376.68     13912464.62
#Sta/Elev= 29
  4636.8   89.96  4651.8   88.83  4671.8   88.36  4700.6   88.91  4761.2   89.24
  4770.6   88.87  4842.3    88.9 4884.94   86.49    4896   86.55 4911.94   86.64
 4965.74   74.98 4969.74   73.78 4991.24   73.27 4995.24    71.2 4996.54   70.62
 4999.64    69.9 5003.14   69.44 5004.74   71.11 5004.84   72.24 5015.24   74.04
 5060.14   87.13 5080.94   87.41  5095.4   89.58  5115.4   88.99  5140.4   87.78
  5160.4   87.82  5190.4   89.17  5205.4   90.21    5294   90.54
#Mann= 5 , 1 , 0
  4636.8     .14       0  4761.2      .1       0    4896     .14       0
 4911.94     .04       0 5060.14      .1       0
#XS Ineff= 2 , 0
       0    4901    86.5    5095       0      90
Permanent Ineff=
       F       F
Bank Sta=4911.94,5060.14
XS Rating Curve= 0
Exp/Cntr=.5,.3

Type RM Length L Ch R = 1 ,98.6    ,0,0,0
BEGIN DESCRIPTION:
Interpolated Cross Section  98.6
END DESCRIPTION:
XS GIS Cut Line= 5
      3101657.79     13912776.37      3101651.27     13912731.07
      3101631.88     13912657.65        3101611.     13912607.15
      3101515.85     13912579.44
#Sta/Elev= 21
 4884.94    86.5  4899.4   86.58 4911.94   86.65 4926.44   83.55 4965.74   74.99
 4969.74   73.79 4991.24   73.28 4995.24   71.21 4996.54   70.63 4999.64   69.91
 5003.14   69.35 5004.74   71.12 5004.84   72.25 5015.24   74.05 5060.14   87.14
 5080.94   87.42  5095.4   89.59  5099.4   89.47  5115.4      89  5140.4   87.79
  5160.4   87.83
#Mann= 5 , 1 , 0
 4884.94     .14       0  4899.4     .07       0 4911.94     .04       0
 5060.14     .07       0  5099.4      .1       0
Bank Sta=4911.94,5060.14
XS Rating Curve= 0
Exp/Cntr=.3,.1

Chan Stop Cuts=-1